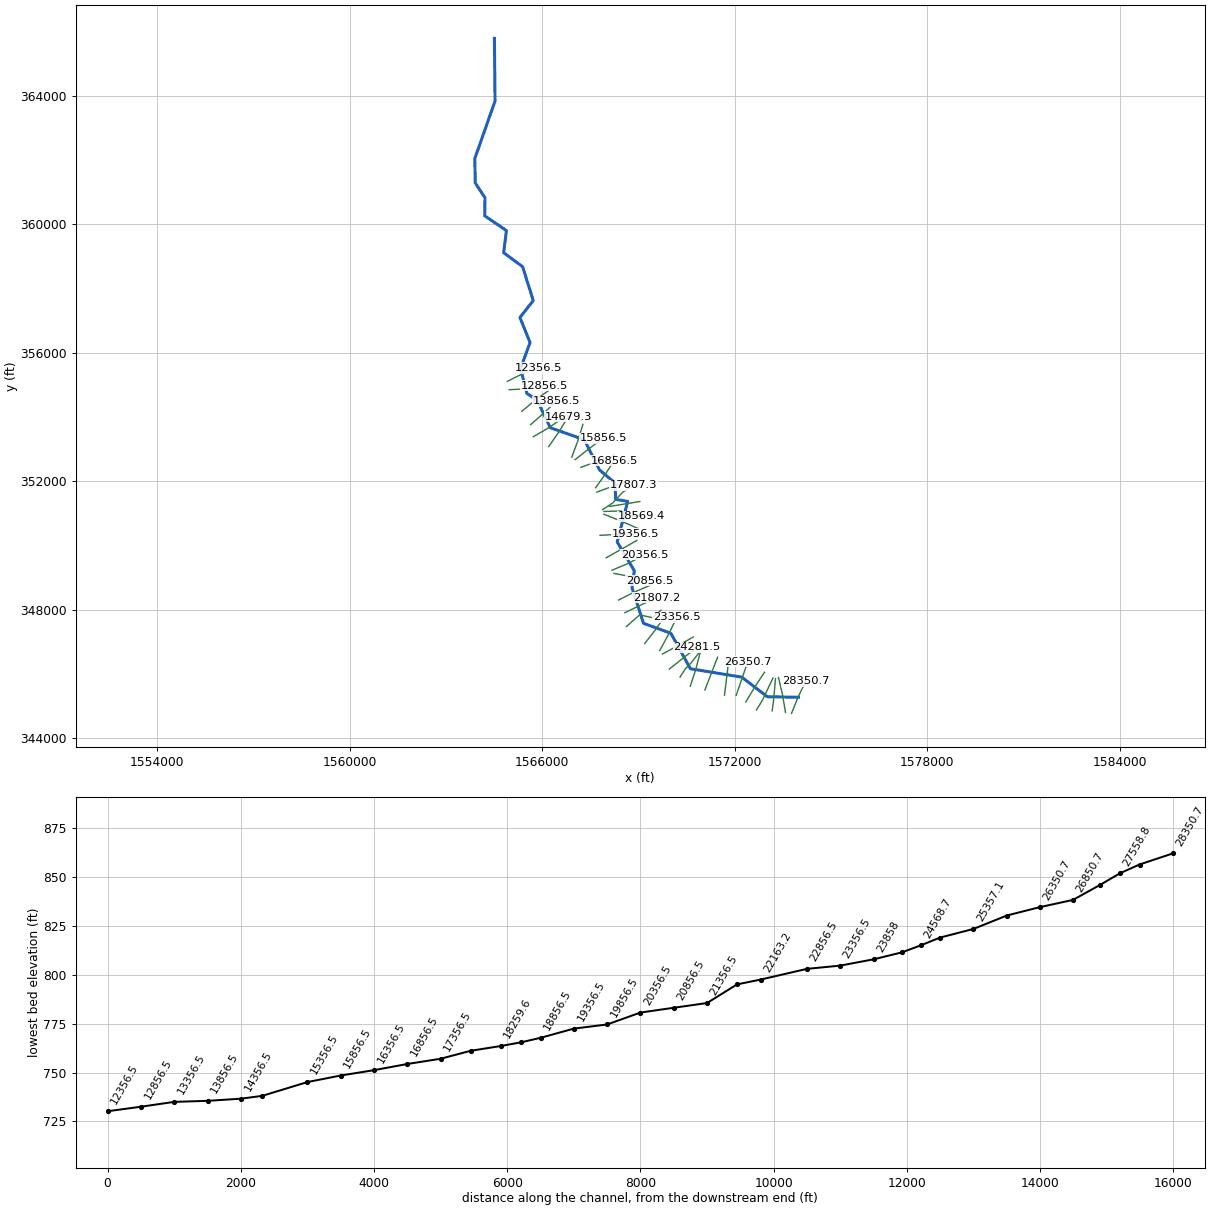
--- MOSESFK.prj (project) ---

Proj Title=MOSESFK
Current Plan=p01
Default Exp/Contr=0,0
English Units
Geom File=g01
Flow File=f01
Plan File=p01
BEGIN DESCRIPTION:
END DESCRIPTION:
DSS Export Rating Curves= 0
DSS Export Rating Curve Sorted= 0
DSS Export Volume Flow Curves= 0
DXF OffsetX= 0
DXF OffsetY= 0
DXF ScaleX= 0
DXF ScaleY= 0

--- MOSESFK.p01 (plan) ---

Plan Title=Floodplain
Program Version=4.00
Geom File=g01
Flow File=f01
K Sum by GR=0
Std Step Tol=0.01
Critical Tol=0.01
Num of Std Step Trials=20
Max Error Tol=0.3
Flow Tol Ratio=0.001
Split Flow NTrial=30
Split Flow Tol=0.02
Split Flow Ratio=0.02
Log Output Level=0
Friction Slope Method=1
Unsteady Friction Slope Method=2
Unsteady Bridges Friction Slope Method=1
Global Log Level=0
CheckData=False
Run HTab=0
Run UNet=0
Run PostProcess=0
UNET Theta=0
UNET Theta Warmup=0
UNET ZTol=0
UNET ZSATol=0
UNET MxIter=0
UNET MaxInSteps=0
UNET DtIC=0
UNET DtMin=0
UNET MaxCRTS=0
UNET WFStab=0
UNET SFStab=0
UNET WFX=0
UNET SFX=0
UNET DSS MLevel=0
UNET DZMax Abort=0
UNET Convert EG Bridges=0
UNET Use Existing IB Tables=0
UNET Froude Limit=0
UNET Froude Power=0
Write IC File=0
Echo Input=False
Echo Output=False
Write Detailed=0

--- MOSESFK.f01 (steady flow) ---

Flow Title=NFF Regression Equation
Program Version=4.00
Number of Profiles= 1
Profile Names=P100yr
River Rch & RM=MOSESFK,Main            ,28350.7
     339
River Rch & RM=MOSESFK,Main            ,27558.8
     374
River Rch & RM=MOSESFK,Main            ,27256.1
     417
River Rch & RM=MOSESFK,Main            ,26350.7
     455
River Rch & RM=MOSESFK,Main            ,24855.8
     474
River Rch & RM=MOSESFK,Main            ,24568.7
     677
River Rch & RM=MOSESFK,Main            ,22163.2
     736
River Rch & RM=MOSESFK,Main            ,18569.4
     814
River Rch & RM=MOSESFK,Main            ,18259.6
     990
River Rch & RM=MOSESFK,Main            ,14679.3
    1052
River Rch & RM=MOSESFK,Main            ,14356.5
    1284
River Rch & RM=MOSESFK,Main            ,9876.3
    1416
River Rch & RM=MOSESFK,Main            ,9561.2
    1585
River Rch & RM=MOSESFK,Main            ,5970.9
    1714
Boundary for River Rch & Prof#=MOSESFK,Main            , 1
Up Type= 0
Dn Type= 1
Dn Known WS=710
DSS Import GetInterval= 0
DSS Import GetPeak= 0
DSS Import FillOption= 0

--- MOSESFK.g01 (geometry) ---

Geom Title=USGS 10m DEM
Program Version=4.00

River Reach=MOSESFK         ,Main
Reach XY= 30
     1573984.274      345272.711     1573017.988      345286.516
     1572217.351      345898.497     1570617.611       346159.24
     1570010.158       347264.21     1569158.101      347573.324
     1568800.941      348679.326     1568872.391      349209.449
     1568339.694      350105.448     1568666.529      351369.044
     1568289.814      351432.315     1568272.309      351941.731
     1567790.326      352346.693     1567311.494      353288.854
      1566253.62      353662.634      1565849.24      354511.151
     1565524.416      354733.385     1565327.216      355504.794
     1565624.137      356314.169     1565308.127      357093.109
     1565723.337      357620.604     1565392.369      358675.531
     1564802.249      359108.678     1564886.497      359800.688
     1564211.305        360258.7      1564220.72      360820.033
     1563915.878        361283.5     1563903.212      362042.238
     1564533.319      363833.123     1564513.985      365783.962

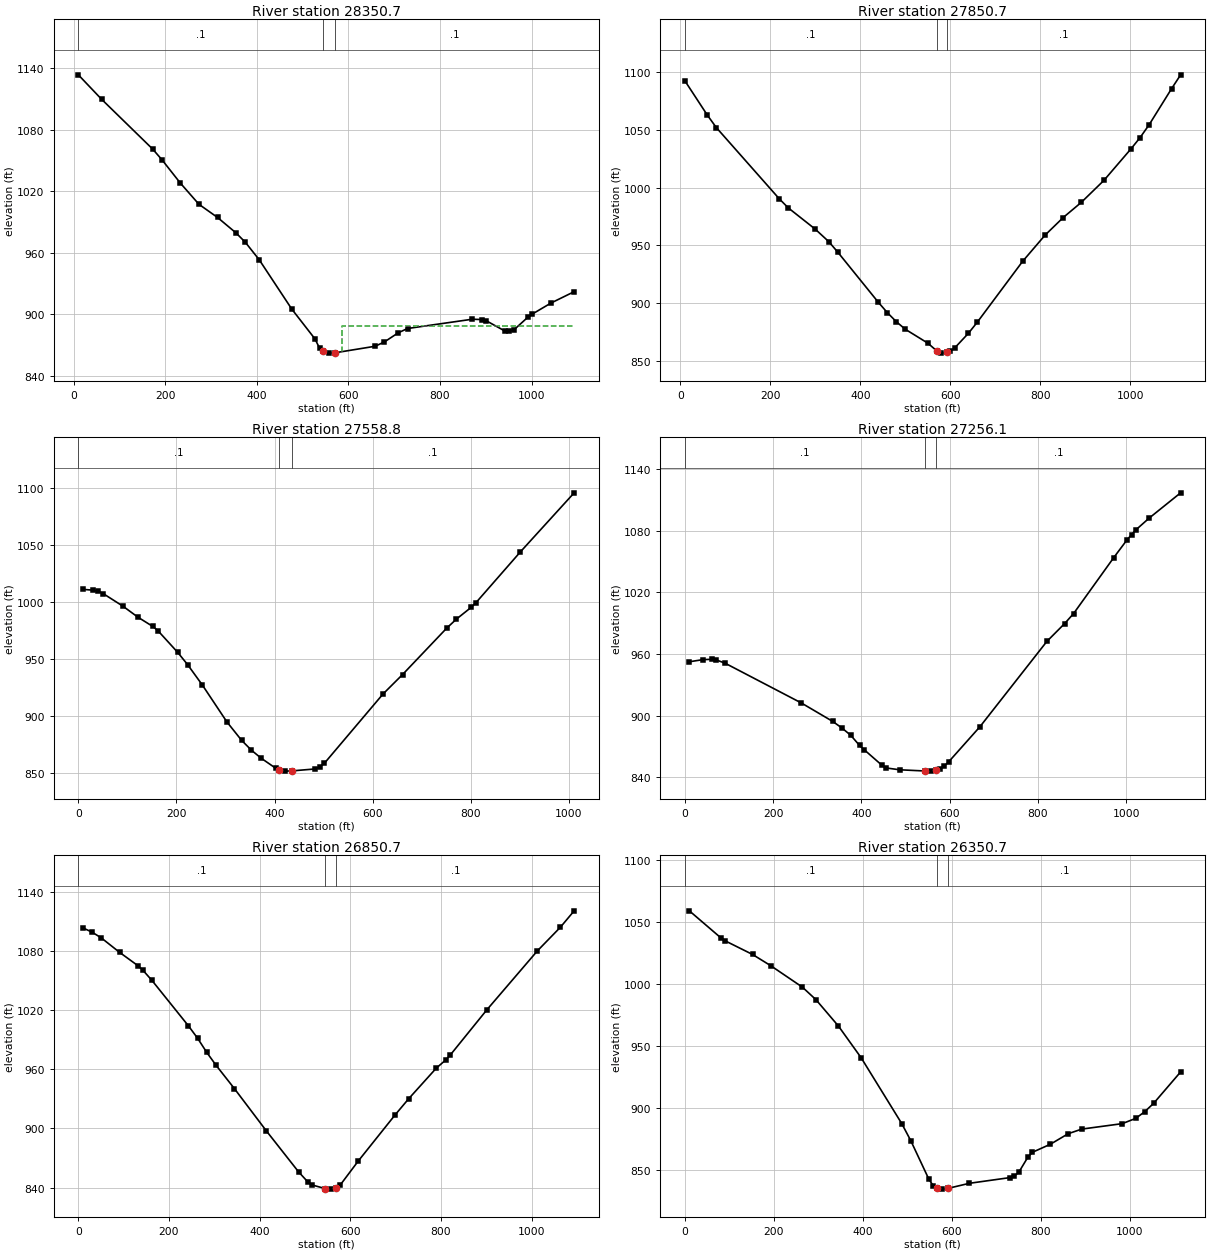
Type RM Length L Ch R = 1 ,28350.7 ,484.7,500,518.5
XS GIS Cut Line= 3
     1573769.594      344770.034     1573975.236      345276.992
     1574208.889      345770.262
#Sta/Elev= 30
    10.1 1133.66    60.8 1109.87   172.2 1061.34   192.5 1050.96     233    1028
   273.5 1007.38   314.1  994.53   354.6  979.41   374.9  970.28   405.2  953.23
   476.2  905.19   526.8  876.11   536.9   867.1   544.7  864.11   557.2  862.21
   569.7  862.47   658.3  868.92   678.5  873.13   708.8  882.05     729  886.23
   870.5  895.28   890.7  894.96   900.8  893.82   941.3  883.83   951.4  883.41
   961.5  884.98   991.8  897.25  1001.9  900.42  1042.4  911.09  1092.9  922.15
#Mann= 3 , 0 , 0
    10.1      .1       0   544.7    .045       0   569.7      .1       0
#XS Ineff= 2 , 0
                          585.77          888.46
Permanent Ineff=
       F       F
Bank Sta=544.7,569.7
XS Rating Curve= 0 ,0
Exp/Cntr=0.3,0.1

Type RM Length L Ch R = 1 ,27850.7 ,299.3,291.8,282.7
XS GIS Cut Line= 3
     1573582.355      344797.992     1573486.511       345359.84
     1573363.546      345887.207
#Sta/Elev= 30
      10 1092.73      60 1062.89      80 1052.08     220  990.26     240  982.41
     300  963.94     330  953.13     350     944     440  900.57     460  891.61
     480  883.74     500  877.19     550  865.15     570  858.39     580  856.53
   592.5  857.13     600  858.27   610.1  861.23   640.2  873.79   660.2  883.56
   760.5   936.1   810.6  958.92   850.7  974.09   890.9  987.24     941 1006.24
  1001.2 1033.61  1021.2 1043.26  1041.3 1054.38  1091.4  1085.8  1111.5  1097.8
#Mann= 3 , 0 , 0
      10      .1       0     570    .045       0   592.5      .1       0
Bank Sta=570,592.5
XS Rating Curve= 0 ,0
Exp/Cntr=0.3,0.1

Type RM Length L Ch R = 1 ,27558.8 ,313.1,302.7,292.2
XS GIS Cut Line= 4
     1573164.511      344846.163     1573201.736      345106.737
     1573232.756      345423.149     1573269.981      345851.235
#Sta/Elev= 30
    10.1 1011.28    30.4  1010.6    40.5 1009.65    50.6 1007.61    91.1  996.53
   121.5  986.94   151.9   978.8     162  975.24   202.5  956.16   222.7  945.42
   253.1  927.36     303  895.14   332.8   879.1   352.6  870.52   372.5  863.47
   402.3  854.64   409.7  853.22   422.2  852.07   434.7  852.25   481.8  853.94
   491.7  855.51   501.7  858.98   621.1  919.59   661.1  936.71     751  977.32
     771  985.31     801  995.57     811   999.8   900.9 1043.97  1010.9 1095.89
#Mann= 3 , 0 , 0
       0      .1       0   409.7    .045       0   434.7      .1       0
Bank Sta=409.7,434.7
XS Rating Curve= 0 ,0
Exp/Cntr=0.3,0.1

Type RM Length L Ch R = 1 ,27256.1 ,408.1,405.5,401.7
XS GIS Cut Line= 3
     1572676.523      344875.329     1572866.711      345187.391
     1573191.051      345872.016
#Sta/Elev= 30
    10.2  952.43    40.6  954.47    60.9  954.84    71.1  954.27    91.4  951.01
   263.9  912.36     335  894.41   355.3  888.18   375.6  881.03   395.8  871.02
   405.9  867.02   446.3  851.81   456.4  849.11   486.7  847.35   544.9  846.15
   557.4  846.04   569.9  846.82   577.6  848.06   587.7  850.95   597.8  855.17
   668.5  889.25     820  972.21   860.4  989.64   880.6  999.34   971.5 1053.75
  1001.8 1071.14  1011.9 1076.16    1022 1080.89  1052.3 1092.39    1123 1116.78
#Mann= 3 , 0 , 0
       0      .1       0   544.9    .045       0   569.9      .1       0
Bank Sta=544.9,569.9
XS Rating Curve= 0 ,0
Exp/Cntr=0.3,0.1

Type RM Length L Ch R = 1 ,26850.7 ,494.2,500,507.1
XS GIS Cut Line= 3
     1572345.563      345125.349     1572620.792      345585.901
     1572927.971      346051.137
#Sta/Elev= 30
    10.1 1103.57    30.4 1099.19    50.6 1093.42    91.1  1078.7   131.6 1065.15
   141.7 1060.95     162 1050.48     243 1004.07   263.2  991.51   283.4  977.13
   303.7   964.2   344.2  940.51     415  897.42   485.9  855.95   506.2  845.78
   516.3  842.54   544.3  838.99   556.8  838.39   569.3  839.57   577.1   842.1
   617.6   866.9   698.7  913.61   729.1  930.24   789.9  961.24   810.2  969.31
   820.3  974.31   901.4 1020.41  1012.9 1080.25  1063.6 1104.21    1094 1120.87
#Mann= 3 , 0 , 0
       0      .1       0   544.3    .045       0   569.3      .1       0
Bank Sta=544.3,569.3
XS Rating Curve= 0 ,0
Exp/Cntr=0.3,0.1

Type RM Length L Ch R = 1 ,26350.7 ,488.7,494.6,500.5
XS GIS Cut Line= 3
      1572045.54      345331.309     1572237.851      345888.093
     1572407.604      346384.792
#Sta/Elev= 30
    10.2 1058.78    81.2 1036.97    91.4 1034.49   152.3 1023.63     193 1014.62
   264.1  997.35   294.5   987.3   345.3  965.94   396.1  940.53   487.5  887.42
   507.8  873.64   548.4  842.63   558.6  837.17   566.4  835.63   578.9  834.68
   591.4  835.29   639.5  839.38   730.4  843.95   740.5  845.17   750.6  848.41
   770.8   860.4   780.9  864.33   821.2   870.8   861.6  879.33   891.9  883.02
   982.7   887.4    1013  891.63  1033.2  896.98  1053.4  903.78    1114  929.06
#Mann= 3 , 0 , 0
       0      .1       0   566.4    .045       0   591.4      .1       0
Bank Sta=566.4,591.4
XS Rating Curve= 0 ,0
Exp/Cntr=0.3,0.1

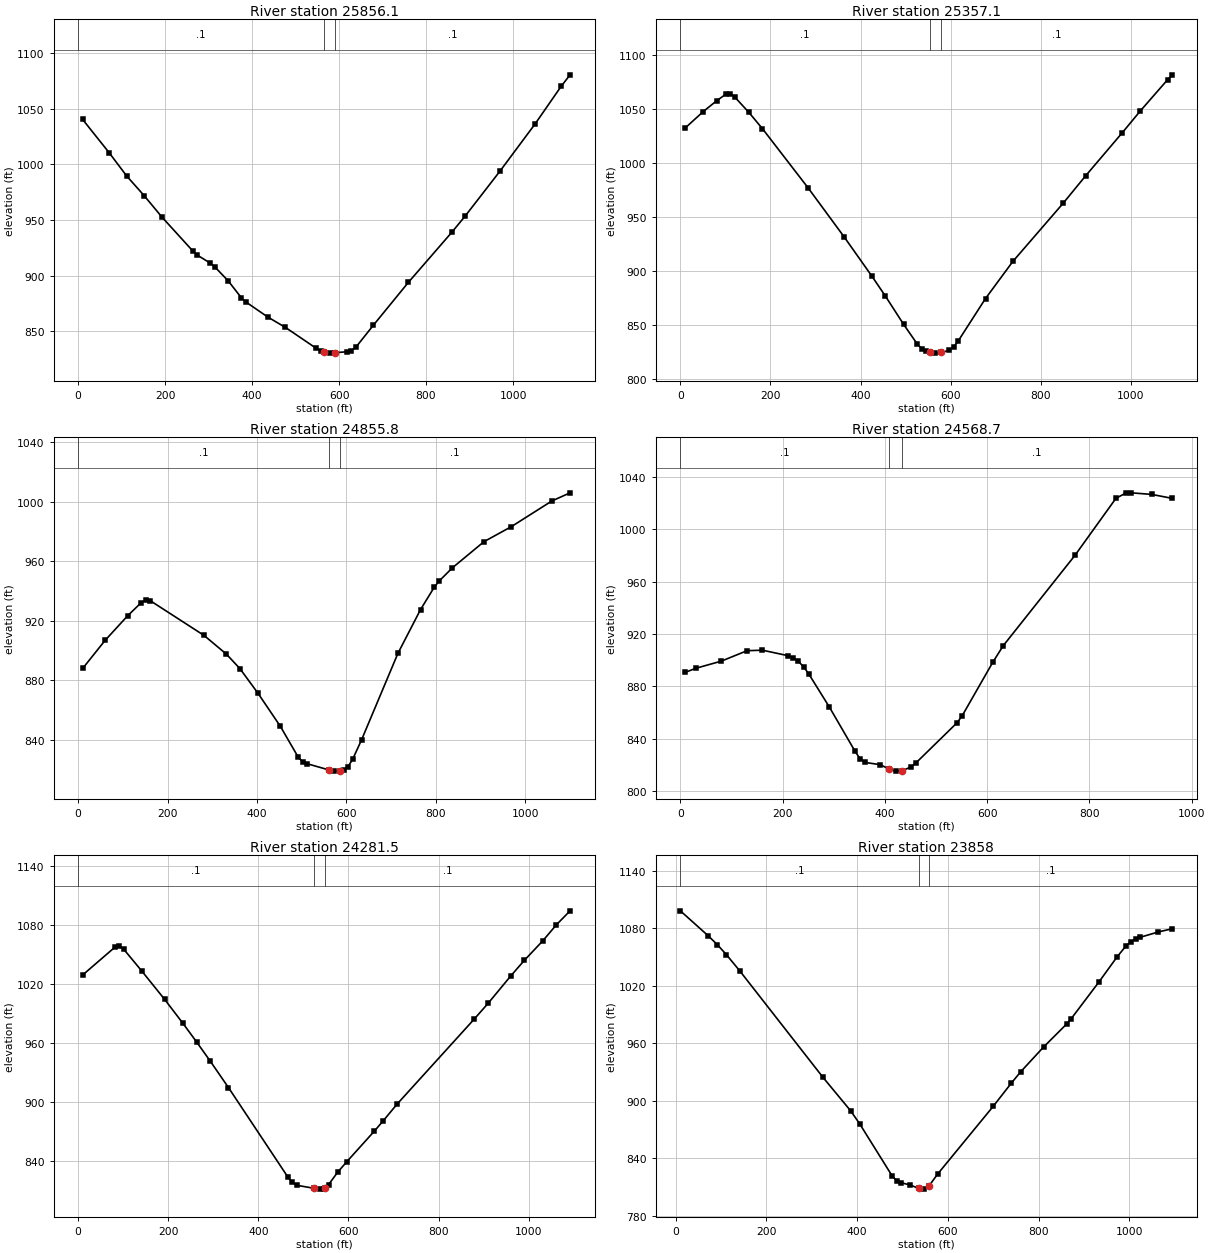
Type RM Length L Ch R = 1 ,25856.1 ,506,499,492
XS GIS Cut Line= 3
     1571681.719       345336.29     1571750.069      345900.258
      1571818.21      346459.242
#Sta/Elev= 30
    10.1 1040.31      71  1010.5   111.6  989.45   152.2  971.61   192.7  952.55
   263.8  922.05   273.9  918.42   304.3  911.09   314.5  907.73   344.9  895.35
   375.3  880.12   385.5  876.38   436.2  862.76   476.8  853.44   547.8  834.62
   557.9  832.36   565.6  831.27   578.2  830.39   590.6  830.76   618.4  831.63
   628.4  832.68   638.5  835.64   678.7  855.35   759.2  893.86   859.7   939.1
   889.9  953.42   970.3  993.95  1050.8  1036.2  1111.1 1070.19  1131.2 1080.27
#Mann= 3 , 0 , 0
       0      .1       0   565.6    .045       0   590.6      .1       0
Bank Sta=565.6,590.6
XS Rating Curve= 0 ,0
Exp/Cntr=0.3,0.1

Type RM Length L Ch R = 1 ,25357.1 ,499.9,501.3,504.5
XS GIS Cut Line= 3
     1571071.365      345500.449     1571268.758      346009.518
     1571466.151      346518.588
#Sta/Elev= 30
    10.1 1031.95    50.6 1047.35    80.9 1057.56   101.1 1063.55   111.2 1064.09
   121.3 1060.68   151.7 1046.88     182 1031.73   283.1  976.99     364  931.04
   424.7  895.17     455  876.53   495.4  850.35   525.8  832.02   535.9  827.63
     546  825.17   553.7  824.14   566.2  823.54   578.7  824.21   596.6  826.03
   606.7  829.32   616.8   834.8   677.4  874.14   738.1  908.52   849.3  962.24
   899.9  988.01   980.8 1027.72  1021.2  1048.1  1081.9 1077.12    1092  1081.5
#Mann= 3 , 0 , 0
       0      .1       0   553.7    .045       0   578.7      .1       0
Bank Sta=553.7,578.7
XS Rating Curve= 0 ,0
Exp/Cntr=0.3,0.1

Type RM Length L Ch R = 1 ,24855.8 ,299.4,287,272.9
XS GIS Cut Line= 3
     1570614.605      345615.477      1570788.02      346140.427
     1570924.812      346670.183
#Sta/Elev= 30
    10.1  888.02    60.3  906.88   110.6  923.34   140.7   932.1   150.8  933.96
   160.8  933.59   281.5   910.2   331.7  897.59   361.9  887.86   402.1   871.4
   452.3  849.12   492.5  828.29   502.6  825.28   512.6  824.04   560.6  819.93
   573.1  819.12   585.6   819.3   593.4  819.82   603.5  822.14   613.6  826.95
   633.9  840.22     715  898.13   765.6  927.55     796  942.42   806.2  946.39
   836.5  955.49   907.5  973.13   968.3  983.14  1059.5 1000.47    1100  1005.9
#Mann= 3 , 0 , 0
       0      .1       0   560.6    .045       0   585.6      .1       0
Bank Sta=560.6,585.6
XS Rating Curve= 0 ,0
Exp/Cntr=0.3,0.1

Type RM Length L Ch R = 1 ,24568.7 ,291.5,287.2,282.7
XS GIS Cut Line= 4
     1570298.193      345900.868     1570459.501      346155.238
     1570633.217      346335.159     1570887.587      346657.775
#Sta/Elev= 30
      10  890.76    30.1  893.81    80.3  899.31   130.5  907.28   160.6  907.66
   210.8  903.45   220.9  901.83   230.9  899.08     241  895.03     251   889.6
   291.2  864.34   341.2  830.67   351.2  824.76   361.2  821.82   391.2   820.1
   408.8   816.6   421.3  815.17   433.8  815.48   451.3  818.39   461.3  821.66
   541.3  852.21   551.3  857.59   611.4  898.66   631.5  911.09   771.8  980.21
   851.9 1023.81     872 1028.01     882 1028.02   922.1 1026.79   962.1 1023.78
#Mann= 3 , 0 , 0
       0      .1       0   408.8    .045       0   433.8      .1       0
Bank Sta=408.8,433.8
XS Rating Curve= 0 ,0
Exp/Cntr=0.3,0.1

Type RM Length L Ch R = 1 ,24281.5 ,428.3,423.5,419.1
XS GIS Cut Line= 3
     1569964.306      346151.659     1570391.969      346491.082
     1570824.442      346824.482
#Sta/Elev= 30
    10.1 1029.29    80.9 1057.25      91 1058.46   101.1 1055.53   141.6 1033.14
   192.1 1004.42   232.6  980.15   262.9  961.25   293.2  941.74   333.7  914.81
   465.1  824.16   475.2  818.44   485.3  815.44   523.4   812.4   535.9  811.53
     546  812.15   548.4  813.11   556.1  816.19   576.3  828.86   596.5  839.47
   657.2  870.32   677.4  881.06   707.8  897.85   879.7  984.63     910 1000.39
   960.6 1028.42   990.9 1044.34  1031.4 1063.96  1061.7 1080.33  1092.1 1094.52
#Mann= 3 , 0 , 0
       0      .1       0   523.4    .045       0   548.4      .1       0
Bank Sta=523.4,548.4
XS Rating Curve= 0 ,0
Exp/Cntr=0.3,0.1

Type RM Length L Ch R = 1 ,23858   ,486.1,501.5,517.9
XS GIS Cut Line= 3
     1569748.982      346617.383     1570229.952      346879.191
     1570707.182      347146.294
#Sta/Elev= 30
    10.1 1098.18      71 1072.37    91.3 1063.05   111.5 1052.57     142 1035.03
   324.5  924.55   385.4  889.73   405.6  875.96   476.6  822.05   486.8  816.69
   496.9  814.66   517.2  812.23   535.1  808.83   547.6  807.99   557.7  811.02
     578  824.15   699.5  894.17     740  918.68   760.3  930.32   810.9  956.21
   861.6  980.14   871.7  985.72   932.5 1023.79     973 1050.27   993.2 1062.01
  1003.4 1065.98  1013.5  1068.8  1023.6 1070.57  1064.1 1076.19  1094.5 1079.52
#Mann= 3 , 0 , 0
    10.1      .1       0   535.1    .045       0   557.7      .1       0
Bank Sta=535.1,557.7
XS Rating Curve= 0 ,0
Exp/Cntr=0.3,0.1

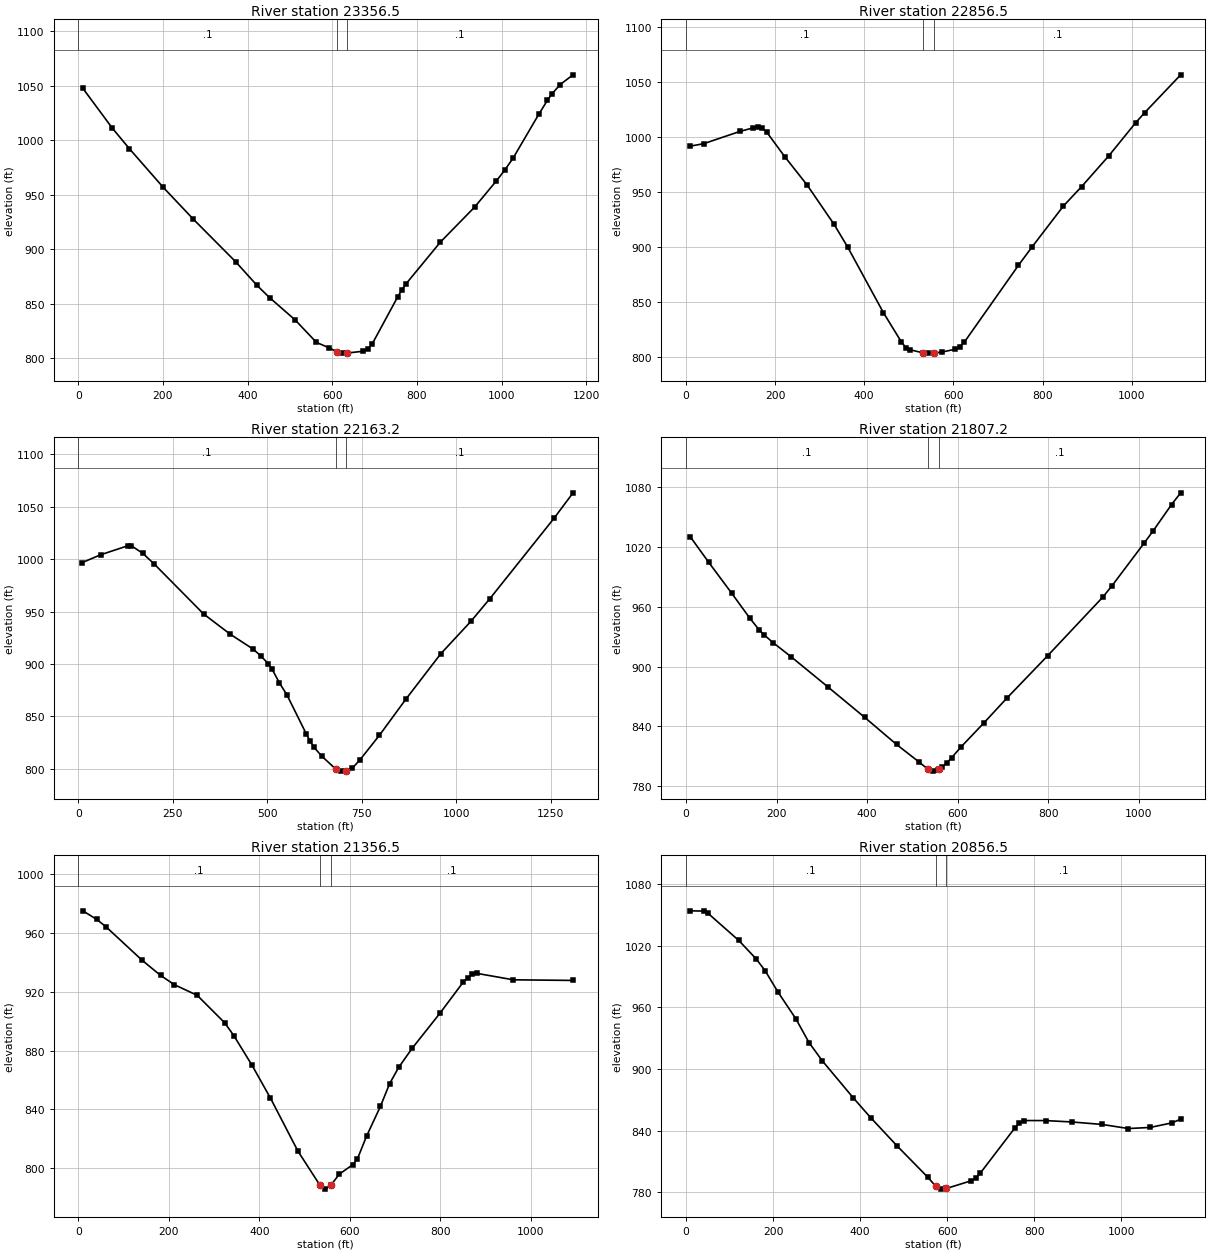
Type RM Length L Ch R = 1 ,23356.5 ,503.4,500,497.3
XS GIS Cut Line= 3
     1569662.979      346725.005     1569961.454      347271.628
     1570193.747      347765.332
#Sta/Elev= 30
      10    1048    80.4 1011.06   120.5   992.3   200.9  956.65   271.2  927.78
   371.7  888.52   421.9  866.94     452  855.57   512.3  835.13   562.5  814.57
   592.7  809.59   610.3  805.96   622.8  804.76   635.3  804.87   673.3  806.51
   683.4  808.28   693.5  812.74   754.2  856.26   764.3   862.8   774.4  868.48
   855.2   906.6     936  938.68   986.6  962.34  1006.8  972.41    1027  983.67
  1087.6 1023.84  1107.8 1036.54  1117.9 1042.13  1138.1 1051.09  1168.4 1059.96
#Mann= 3 , 0 , 0
       0      .1       0   610.3    .045       0   635.3      .1       0
Bank Sta=610.3,635.3
XS Rating Curve= 0 ,0
Exp/Cntr=0.3,0.1

Type RM Length L Ch R = 1 ,22856.5 ,724.6,693.4,660.3
XS GIS Cut Line= 3
     1569193.854      346943.166     1569529.865      347370.609
     1569851.494      347836.563
#Sta/Elev= 30
    10.1  991.53    40.3  993.82   120.8 1004.88     151 1008.19   161.1 1008.81
   171.2 1007.61   181.2 1004.31   221.5  982.05   271.9  956.13   332.3  920.35
   362.5   899.9     443  839.95   483.3  813.33   493.4  808.12   503.4   806.1
   531.2  803.44   543.7   803.1   556.2  803.19     574  804.04   604.4  806.67
   614.5  808.85   624.6  813.12   745.9  883.01   776.2  899.61     847   937.1
   887.5  954.62   948.1  982.44  1008.8 1012.77    1029 1021.95  1109.9 1056.44
#Mann= 3 , 0 , 0
       0      .1       0   531.2    .045       0   556.2      .1       0
Bank Sta=531.2,556.2
XS Rating Curve= 0 ,0
Exp/Cntr=0.3,0.1

Type RM Length L Ch R = 1 ,22163.2 ,337.7,356,373.9
XS GIS Cut Line= 4
     1568623.728      347471.982      1569038.75      347836.563
     1569435.816      347749.705     1569701.148      347978.053
#Sta/Elev= 30
      10  996.74    60.3 1004.34   130.6 1012.75   140.6 1012.75   170.7 1005.58
   200.9  995.38   331.4  947.74   401.8  928.41     462  914.26   482.1  907.94
   502.2  900.38   512.2  895.27   532.3  881.84   552.4  870.14   603.2  833.17
   613.4  826.17   623.5  820.42   643.9  812.03   682.2  799.21   694.7  797.63
   707.2  797.96   725.2   800.5   745.5  808.54   796.3  831.67   867.4  866.68
   958.9  909.65  1038.9  940.72  1088.9   962.3  1258.9 1039.17  1308.9 1063.35
#Mann= 3 , 0 , 0
       0      .1       0   682.2    .045       0   707.2      .1       0
Bank Sta=682.2,707.2
XS Rating Curve= 0 ,0
Exp/Cntr=0.3,0.1

Type RM Length L Ch R = 1 ,21807.2 ,450.2,450.7,449.9
XS GIS Cut Line= 3
     1568577.603      347904.416     1569069.771      348140.567
     1569565.614      348370.209
#Sta/Elev= 30
    10.1 1029.97    50.5 1004.53   101.1  973.62   141.5  948.32   161.7  936.92
   171.9  932.17   192.1  924.17   232.5   909.8   313.4  879.66   394.3  849.22
     465   821.9   515.6  803.99   533.4  797.34   535.8   796.5   545.9  795.15
     556  796.18   558.4  796.93   566.1  799.35   576.2   803.5   586.4  808.46
   606.6  819.06   657.2  843.21   707.8  868.03   798.9  911.07   920.3  969.69
   940.5  981.02  1011.4  1023.8  1031.6 1036.25  1072.1 1062.59  1092.3 1074.37
#Mann= 3 , 0 , 0
       0      .1       0   533.4    .045       0   558.4      .1       0
Bank Sta=533.4,558.4
XS Rating Curve= 0 ,0
Exp/Cntr=0.3,0.1

Type RM Length L Ch R = 1 ,21356.5 ,518,500,482.9
XS GIS Cut Line= 3
     1568380.596      348298.748     1568868.325      348543.715
     1569371.075      348759.703
#Sta/Elev= 30
    10.1  975.14    40.4  969.35    60.6  964.45   141.5  941.34   181.9  931.14
   212.3  924.83   262.8  917.58   323.4  898.89   343.6  890.17   384.1  869.82
   424.5  847.62   485.1  811.56   533.3  788.53   545.8   785.6   558.3  788.28
   576.2  795.69   606.6  802.31   616.7  806.21     637  821.78   667.4  841.88
   687.7  857.36   707.9  868.57   738.3  881.79   799.1  905.43   849.8  926.33
   859.9  929.56     870  931.82   880.2  932.57   961.2  928.16    1093  927.74
#Mann= 3 , 0 , 0
       0      .1       0   533.3    .045       0   558.3      .1       0
Bank Sta=533.3,558.3
XS Rating Curve= 0 ,0
Exp/Cntr=0.3,0.1

Type RM Length L Ch R = 1 ,20856.5 ,484,500,519.7
XS GIS Cut Line= 3
     1568238.415      349127.027     1568814.068      349019.262
     1569352.298      348902.785
#Sta/Elev= 30
    10.1 1053.97    40.4 1053.73    50.5 1051.64   121.2 1025.21   161.6 1007.08
   181.8  995.78     212  974.57   252.4  948.98   282.7  925.79     313  908.15
   383.7  872.31   424.1  852.83   484.7  825.35   555.4   794.8   573.2  786.27
   585.7  783.18   598.2   783.8   655.7  791.39   665.8  794.08   675.8  798.58
   755.9  842.96   765.9  847.49   775.9  849.91     826  849.88     886  848.54
   956.1  846.11  1016.2  842.13  1066.3   843.2  1116.3  847.66  1136.3  851.23
#Mann= 3 , 0 , 0
       0      .1       0   573.2    .045       0   598.2      .1       0
Bank Sta=573.2,598.2
XS Rating Curve= 0 ,0
Exp/Cntr=0.3,0.1

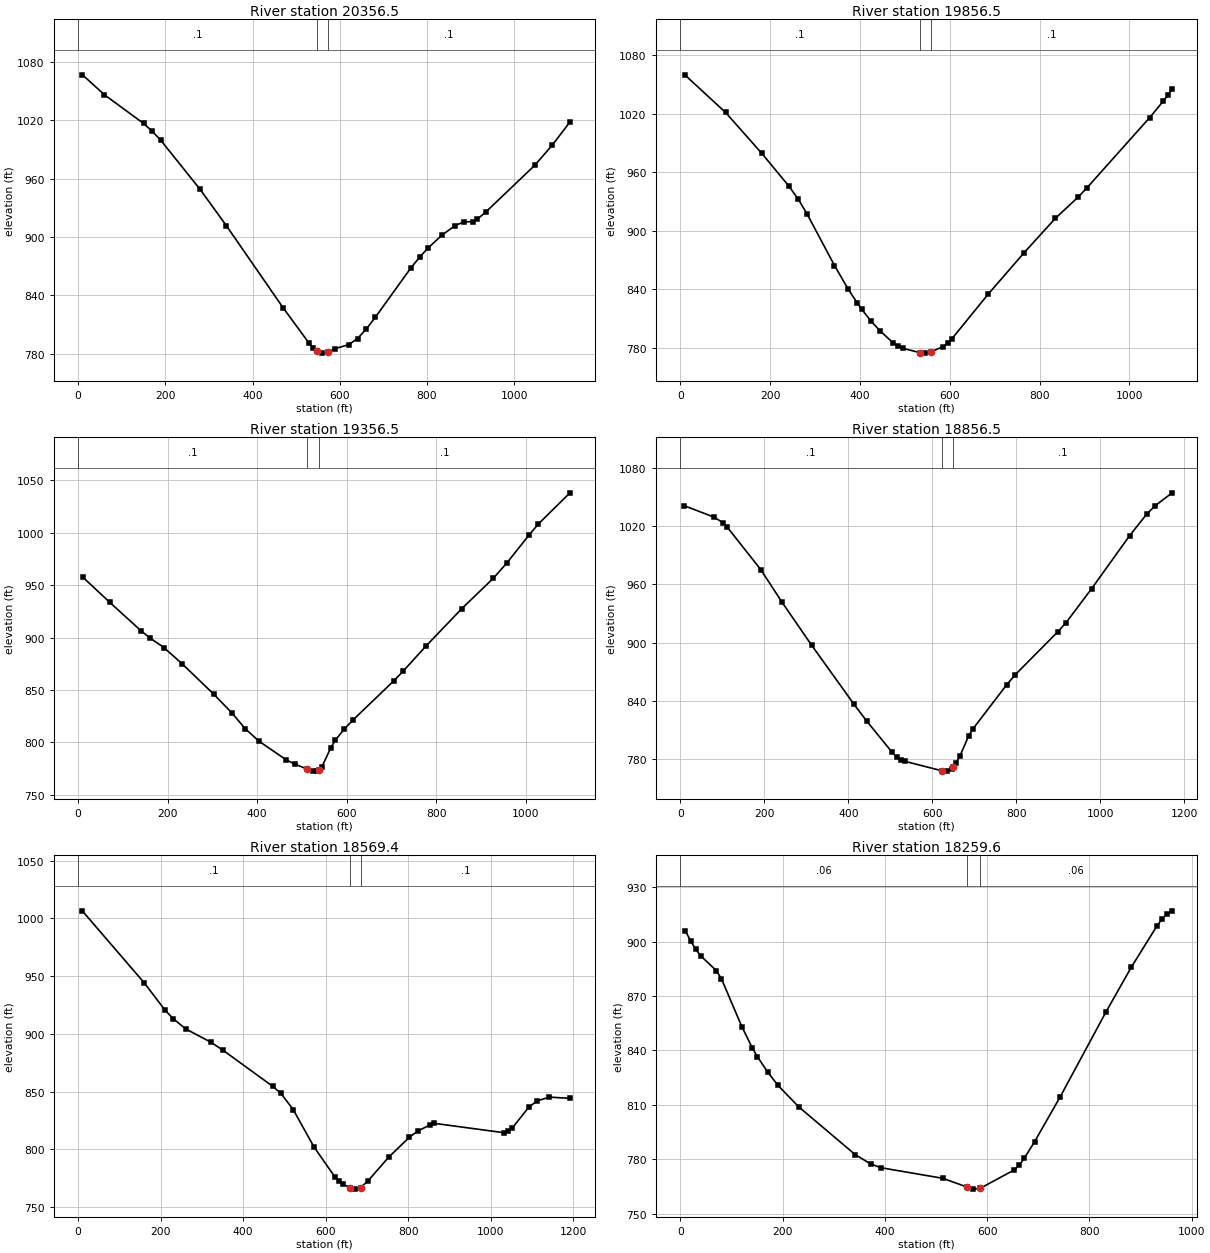
Type RM Length L Ch R = 1 ,20356.5 ,496.8,500,500.5
XS GIS Cut Line= 3
     1568176.373      349226.293     1568693.008      349441.956
     1569193.386      349711.707
#Sta/Elev= 30
      10 1066.74      60 1046.34     150 1016.81     170 1008.72   189.9  999.28
   279.9  948.97   339.9   911.8   469.9  827.51   529.8  790.94   539.8  785.68
   547.3  782.99   559.8  780.73   572.3  781.81   590.3  785.44   620.7   789.5
     641  795.76   661.4  805.73   681.7   817.5   762.9  868.09   783.2  879.29
   803.5  889.12   833.9   901.7   864.4  911.78   884.7   915.6     905  915.82
   915.1  918.16   935.4  925.87  1047.1  973.59  1087.7  994.53  1128.3 1018.36
#Mann= 3 , 0 , 0
       0      .1       0   547.3    .045       0   572.3      .1       0
Bank Sta=547.3,572.3
XS Rating Curve= 0 ,0
Exp/Cntr=0.3,0.1

Type RM Length L Ch R = 1 ,19856.5 ,512.6,500,486.6
XS GIS Cut Line= 3
     1567996.952      349614.521     1568472.342       349881.74
     1568950.416      350153.083
#Sta/Elev= 30
    10.1 1059.82     101 1021.22   181.8   979.2   242.4  945.46   262.6  932.43
   282.8  916.89   343.4  864.41   373.7  840.33   393.9  826.13     404  819.61
   424.2   807.7   444.4  797.64   474.7  784.83   484.8  781.45   494.9  779.64
   532.8  775.23   545.3  774.63   557.8  775.87   585.3  781.35   595.3  784.65
   605.3  789.62   685.3  834.92   765.2  877.36   835.2   912.8   885.2  934.24
   905.2   943.9  1045.1 1015.97  1075.1 1032.69  1085.1 1038.64  1095.1 1045.31
#Mann= 3 , 0 , 0
       0      .1       0   532.8    .045       0   557.8      .1       0
Bank Sta=532.8,557.8
XS Rating Curve= 0 ,0
Exp/Cntr=0.3,0.1

Type RM Length L Ch R = 1 ,19356.5 ,512.1,500,487.6
XS GIS Cut Line= 3
     1567804.124      350312.019     1568338.014      350342.965
     1568902.259      350361.653
#Sta/Elev= 30
    10.1   957.8    70.6  933.61   141.3   906.2   161.4  899.28   191.7  890.48
   232.1  875.08   302.7  846.09   343.1   828.3   373.3  813.09   403.6  801.27
   464.2  783.49   484.3  779.19   512.2  774.44   524.7  772.51   534.8  772.62
   537.2  773.61   544.9   776.8     565  795.03   575.1  802.23   595.3  812.96
   615.4  821.78   706.2  858.99   726.3  867.87   776.7  891.57   857.4  927.57
     928  956.63   958.2  971.21  1008.6  998.28  1028.8 1008.52  1099.3 1038.13
#Mann= 3 , 0 , 0
       0      .1       0   512.2    .045       0   537.2      .1       0
Bank Sta=512.2,537.2
XS Rating Curve= 0 ,0
Exp/Cntr=0.3,0.1

Type RM Length L Ch R = 1 ,18856.5 ,288.4,287.1,286.5
XS GIS Cut Line= 3
     1567928.207      350969.659     1568517.459      350730.596
      1569007.73      350516.756
#Sta/Elev= 30
    10.1 1040.81    80.7  1029.1   100.9 1023.54     111 1019.31   191.8  975.09
   242.2  941.63   312.9  897.26   413.8  836.43   444.1  819.17   504.7  786.96
   514.8  782.45   524.9  779.51     535  777.84   623.4  768.08   635.9  767.79
     646   770.2   648.4  771.53   656.1  775.79   666.2  783.82   686.4  803.99
   696.5  811.17   777.2  856.77   797.4  867.01   898.3  911.02   918.5  920.69
     979  955.43  1069.9 1010.24  1110.2  1032.2  1130.4 1040.88  1170.8 1054.17
#Mann= 3 , 0 , 0
       0      .1       0   623.4    .045       0   648.4      .1       0
Bank Sta=623.4,648.4
XS Rating Curve= 0 ,0
Exp/Cntr=0.3,0.1

Type RM Length L Ch R = 1 ,18569.4 ,293.2,309.8,326.7
XS GIS Cut Line= 4
     1567928.207      351056.518     1568449.356      351068.926
     1568759.564       350926.23     1569088.384      350907.618
#Sta/Elev= 30
      10 1006.44   160.4  944.02   210.5  920.49   230.6  913.02   260.6  904.25
   320.8  892.87   350.9  885.82   471.2  854.62   491.2  848.53   521.3  834.37
   571.5  802.09   621.7  776.39   631.8  772.35   641.8  769.77   659.4  766.69
   671.9  765.53   684.4  766.81   702.1  772.51   752.3  793.05   802.5  810.35
   822.6  815.67   852.7  821.13   862.8  822.49  1032.4  814.34  1042.4  815.52
  1052.4   818.5  1092.3  836.52  1112.3  841.86  1142.2  845.18  1192.1   844.1
#Mann= 3 , 0 , 0
       0      .1       0   659.4    .045       0   684.4      .1       0
Bank Sta=659.4,684.4
XS Rating Curve= 0 ,0
Exp/Cntr=0.3,0.1

Type RM Length L Ch R = 1 ,18259.6 ,432.5,452.3,470.7
XS GIS Cut Line= 3
     1568095.719      351211.621     1568652.069      351300.086
     1569044.954      351366.725
#Sta/Elev= 30
    10.1  905.93    20.1  900.42    30.2   895.8    40.2  892.12    70.4  884.04
    80.5  879.54   120.7  852.98   140.8  841.44   150.9  836.57     171  828.07
   191.1  820.76   231.4  809.02     342  782.64   372.2  777.51   392.3   775.4
     513  769.58   560.8  764.75   573.3   763.6   585.8  763.95     653  774.17
     663  776.81   672.9  780.69   692.9  789.76   742.7  814.33   832.3  861.15
   882.1  885.94   931.9  908.52   941.9  912.41   951.9  915.31   961.8  916.95
#Mann= 3 , 0 , 0
       0     .06       0   560.8    .045       0   585.8     .06       0
Bank Sta=560.8,585.8
XS Rating Curve= 0 ,0
Exp/Cntr=0.3,0.1

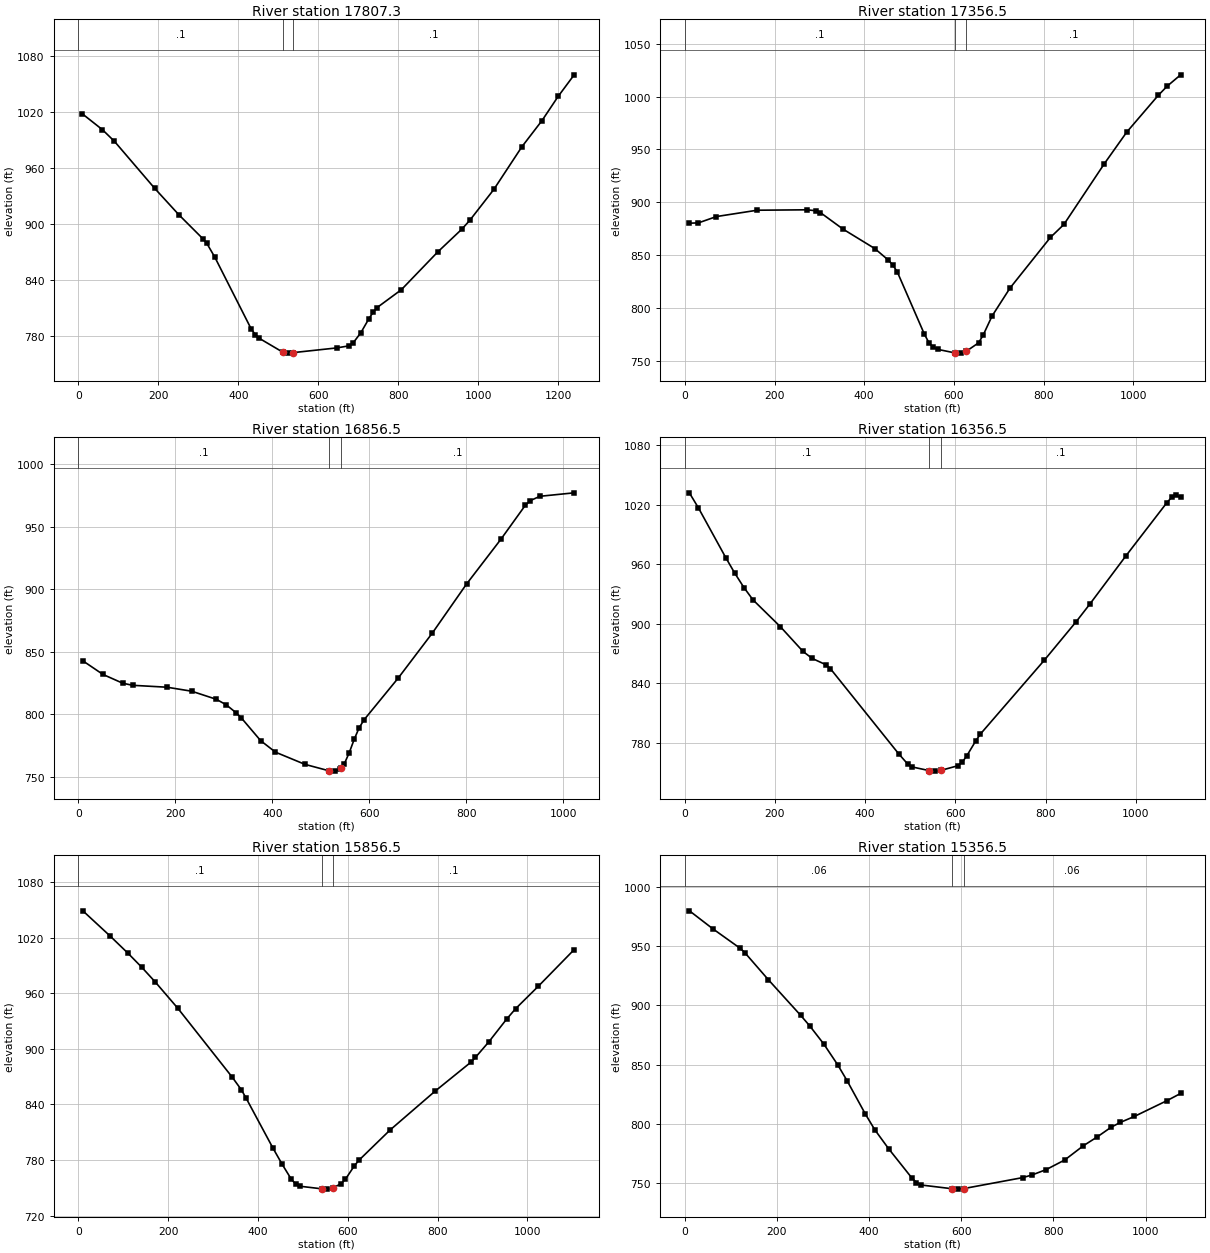
Type RM Length L Ch R = 1 ,17807.3 ,463.6,450.7,435.8
XS GIS Cut Line= 4
     1567884.605      351112.525     1568194.986      351317.092
     1568505.193      351652.116     1568854.136      351870.832
#Sta/Elev= 30
      10 1018.13    60.3 1001.09    90.4  988.55   190.9  938.14   251.2  909.85
   311.5  883.98   321.5  878.92   341.6     864   432.6  786.91   442.8  780.97
   452.9  776.97   511.4  762.18   523.9  761.15   536.4  761.65   645.7  766.72
   676.1  768.91   686.3  771.55   706.6  783.09   726.9  798.23     737  804.81
   747.1  810.03     808  829.29   898.6  869.67   958.9  894.16     979  903.72
  1039.2  936.95  1109.6  982.91  1159.8 1010.96    1200 1036.81  1240.1 1060.02
#Mann= 3 , 0 , 0
       0      .1       0   511.4    .045       0   536.4      .1       0
Bank Sta=511.4,536.4
XS Rating Curve= 0 ,0
Exp/Cntr=0.3,0.1

Type RM Length L Ch R = 1 ,17356.5 ,483.5,500,519.8
XS GIS Cut Line= 3
     1567704.858       351658.32     1568282.126      351870.173
     1568753.359      352005.753
#Sta/Elev= 30
    10.1  880.14    30.2  880.41    70.6  886.42   161.3  892.41   272.2  892.81
   292.3  891.91   302.4  890.13   352.8  874.49   423.4  856.14   453.6  845.22
   463.7  840.56   473.8  833.89   534.3  774.82   544.4  766.85   554.4  762.57
   564.5  760.58   602.4  757.28   614.9  757.08   627.4   758.8   654.9  766.84
     665  774.04     685  792.25     725  818.72   815.1  866.68   845.1  878.94
   935.1  936.37   985.2   966.4  1055.2 1001.09  1075.2 1009.85  1105.3 1020.63
#Mann= 3 , 0 , 0
       0      .1       0   602.4    .045       0   627.4      .1       0
Bank Sta=602.4,627.4
XS Rating Curve= 0 ,0
Exp/Cntr=0.3,0.1

Type RM Length L Ch R = 1 ,16856.5 ,516.8,500,481.9
XS GIS Cut Line= 3
     1567667.633      351794.811     1567974.504      352225.078
     1568244.619      352638.576
#Sta/Elev= 30
    10.2  842.47    50.8   831.8    91.5  824.79   111.8  823.11   182.9  821.57
   233.8  818.37   284.6   811.9   304.9   807.5   325.2  801.17   335.4  797.33
     376  778.78   406.5  769.58   467.5  759.79     516  754.76   528.5   754.4
   538.6  755.93     541     757   548.6  760.39   558.7  769.22   568.8  779.82
   578.9  788.97     589  795.41   659.5  828.85   730.1     865   800.6  904.23
   871.2  939.95   921.6  967.16   931.7  970.91   951.8  974.42  1022.4  977.19
#Mann= 3 , 0 , 0
       0      .1       0     516    .045       0     541      .1       0
Bank Sta=516,541
XS Rating Curve= 0 ,0
Exp/Cntr=0.3,0.1

Type RM Length L Ch R = 1 ,16356.5 ,491.1,500,508.3
XS GIS Cut Line= 3
     1567209.215      352430.398     1567731.128      352618.302
     1568244.619      352799.884
#Sta/Elev= 30
    10.1 1032.15    30.3 1016.88    90.8  966.75   110.9  950.97   131.1  936.57
   151.3  924.06   211.8  897.09   262.2  872.02   282.4  865.01   312.7  858.67
   322.7  854.74     474  768.86   494.2  758.41   504.3  755.44   542.2  751.73
   554.7  751.24   567.2  751.91   605.1  756.63   615.2  760.27   625.3  766.73
   645.5  782.01   655.6  788.75   796.8  863.01   867.4  901.85   897.6  919.53
   978.3  968.64  1069.1 1022.32  1079.2 1027.48  1089.3 1029.46  1099.4 1027.58
#Mann= 3 , 0 , 0
       0      .1       0   542.2    .045       0   567.2      .1       0
Bank Sta=542.2,567.2
XS Rating Curve= 0 ,0
Exp/Cntr=0.3,0.1

Type RM Length L Ch R = 1 ,15856.5 ,482.6,500,519.2
XS GIS Cut Line= 3
     1567027.183      352668.085     1567462.649      353011.578
     1567903.927      353339.232
#Sta/Elev= 30
    10.1 1049.16    70.6 1022.02   110.9 1003.19   141.2  988.22   171.4  972.26
   221.9  943.69   342.9  869.35     363  855.87   373.1  847.32   433.6   792.7
   453.8  775.46     474  759.47     484  753.96   494.1  751.59   542.1  748.84
   554.6   748.5   567.1  749.95   584.6  754.15   594.6  759.01   614.6  773.54
   624.6  779.53   694.5  812.46   794.5  854.31   874.4  885.66   884.4  890.78
   914.4  907.69   954.4  932.49   974.3  943.61  1024.3  967.58  1104.3 1007.25
#Mann= 3 , 0 , 0
       0      .1       0   542.1    .045       0   567.1      .1       0
Bank Sta=542.1,567.1
XS Rating Curve= 0 ,0
Exp/Cntr=0.3,0.1

Type RM Length L Ch R = 1 ,15356.5 ,683.1,677.2,669.6
XS GIS Cut Line= 3
     1566925.258       352748.91     1567130.572      353305.579
     1567270.567      353767.731
#Sta/Elev= 30
    10.1  979.81    60.3  964.81   120.7  948.07   130.7  944.36     181  921.87
   251.4  891.72   271.5  882.63   301.7   867.5   331.9  849.97     352  836.74
   392.2  808.26   412.3  795.27   442.5  779.17   492.8  754.58   502.8   750.7
   512.9  748.63   580.8  745.45   593.3  745.15   605.8  745.64   734.2  754.92
   754.3  757.18   784.5  761.64   824.7  769.74     865   781.7   895.1  789.16
   925.3  797.33   945.4  801.42   975.6  806.41    1046  819.65  1076.2  825.82
#Mann= 3 , 0 , 0
       0     .06       0   580.8    .045       0   605.8     .06       0
Bank Sta=580.8,605.8
XS Rating Curve= 0 ,0
Exp/Cntr=0.3,0.1

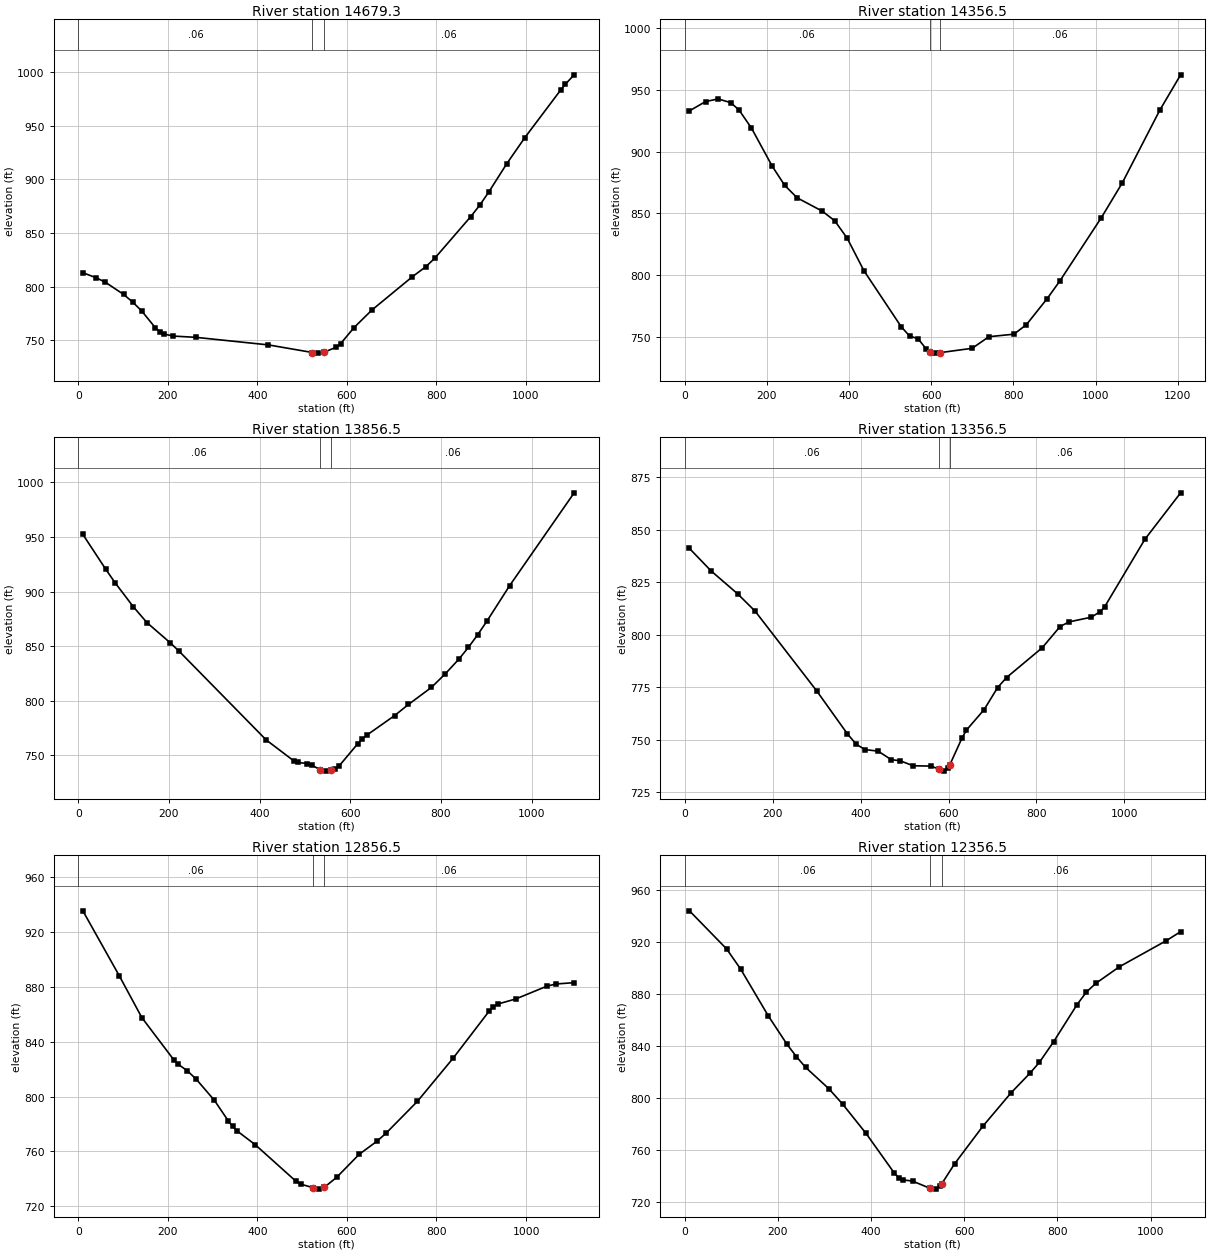
Type RM Length L Ch R = 1 ,14679.3 ,333.6,322.8,316.2
XS GIS Cut Line= 3
     1566205.405      353076.138     1566516.194       353524.89
      1566811.46      354003.489
#Sta/Elev= 30
    10.1  813.06    40.4  808.24    60.7  804.08   101.1  792.83   121.3  785.76
   141.5  777.46   171.8  761.92     182  758.09   192.1  755.86   212.3  753.98
   262.8   752.8   424.6  745.77   523.3  738.67   535.8  738.09   548.3  738.75
     576  743.55     586  746.81   616.2   761.9   656.3  778.32   746.7  809.34
   776.8  818.67   796.9  826.67   877.3  865.44   897.3  876.04   917.4  888.28
   957.6  914.68   997.8  938.86  1078.1  983.36  1088.1  988.59  1108.2   997.5
#Mann= 3 , 0 , 0
       0     .06       0   523.3    .045       0   548.3     .06       0
Bank Sta=523.3,548.3
XS Rating Curve= 0 ,0
Exp/Cntr=0.3,0.1

Type RM Length L Ch R = 1 ,14356.5 ,495.9,500,499.1
XS GIS Cut Line= 3
     1565725.734      353383.074     1566243.138      353683.107
     1566736.907      354039.388
#Sta/Elev= 30
    10.1  932.85    50.7  940.62    81.1  942.75   111.5  939.76   131.8  933.89
   162.2  919.15   212.9  888.13   243.3  872.62   273.7  862.51   334.5  851.78
   364.9  843.97   395.4  829.77   435.9  803.54   527.1  757.91   547.4  750.42
   567.7  748.39     588  739.82   595.8  737.74   608.3  736.63   620.8  736.99
   699.6  740.54   740.2  749.94   801.1  751.99   831.5  759.68   882.3   780.9
   912.7  794.99  1014.2  846.57  1064.9  874.63  1156.2  933.56    1207  962.29
#Mann= 3 , 0 , 0
       0     .06       0   595.8    .045       0   620.8     .06       0
Bank Sta=595.8,620.8
XS Rating Curve= 0 ,0
Exp/Cntr=0.3,0.1

Type RM Length L Ch R = 1 ,13856.5 ,500.7,500,496.4
XS GIS Cut Line= 3
     1565642.328       353758.46     1566051.711      354119.345
     1566454.722      354491.233
#Sta/Elev= 30
    10.1  952.33    60.6  920.41    80.9  908.23   121.3  886.15   151.6  871.52
   202.1  853.37   222.3  845.42   414.4  764.16     475  745.08   485.1  743.44
   505.3  742.48   515.4  740.98   533.2   736.9   545.7  735.53   558.2  736.36
   566.1  737.58   576.2  740.64   616.8  760.75     627  765.18   637.1  768.64
   698.1  786.49   728.5  796.61   779.3   812.3   809.8  824.69   840.2  838.37
   860.6  848.84   880.9  860.29   901.2  872.71   951.9  905.57  1094.1  990.51
#Mann= 3 , 0 , 0
       0     .06       0   533.2    .045       0   558.2     .06       0
Bank Sta=533.2,558.2
XS Rating Curve= 0 ,0
Exp/Cntr=0.3,0.1

Type RM Length L Ch R = 1 ,13356.5 ,518.1,500,487.2
XS GIS Cut Line= 3
     1565368.465      354173.139     1565820.916      354551.482
     1566261.412      354860.836
#Sta/Elev= 30
      10  841.27      60   830.4     120  819.54   159.9  811.27   299.9   773.3
   369.9  752.78   389.9  747.85   409.9  745.27   439.8  744.53   469.8  740.45
   489.8  739.95   519.8  737.54   559.8  737.41   577.3  736.05   589.8     735
   599.9  736.62   602.3  737.69   630.4  750.64   640.6  754.51   681.2  764.36
   711.7  774.83     732   779.6   813.2  793.81   853.9  803.93   874.2  806.13
   924.9  808.37   945.3  811.06   955.4  813.37  1046.8  845.51  1128.1  867.65
#Mann= 3 , 0 , 0
       0     .06       0   577.3    .045       0   602.3     .06       0
Bank Sta=577.3,602.3
XS Rating Curve= 0 ,0
Exp/Cntr=0.3,0.1

Type RM Length L Ch R = 1 ,12856.5 ,488.6,500,505
XS GIS Cut Line= 3
     1564973.831      354845.419     1565510.116      354873.698
     1566073.166      354965.133
#Sta/Elev= 30
    10.1   935.5    91.2  888.28   141.9   857.6   212.8  827.01   222.9  823.57
   243.2  818.91   263.4  812.67     304  797.25   334.4  782.56   344.5  778.22
   354.6  774.97   395.2   764.9   486.4  738.16   496.5  736.18   524.5  733.57
     537  732.52   549.5  733.89   577.1  741.13   627.1  757.85   667.1  767.48
   687.1  773.23   757.2  796.47   837.3  828.08   917.3  862.21   927.3  865.46
   937.3  867.53   977.4  871.26  1047.4  880.64  1067.4  882.15  1107.5  883.11
#Mann= 3 , 0 , 0
       0     .06       0   524.5    .045       0   549.5     .06       0
Bank Sta=524.5,549.5
XS Rating Curve= 0 ,0
Exp/Cntr=0.3,0.1

Type RM Length L Ch R = 1 ,12356.5 ,531.1,500,474.2
XS GIS Cut Line= 3
     1564916.359      355105.812     1565398.334      355346.601
     1565893.246      355523.506
#Sta/Elev= 30
      10  943.84    89.8  914.57   119.7  899.23   179.6     863   219.5  841.34
   239.5  831.95   259.4  823.65   309.3  807.27   339.2  795.31   389.1  772.98
     449  742.93     459  738.97   468.9  737.29   488.9  736.38   526.3  730.86
   538.8  730.21   548.9  732.83   551.3  734.14   579.2  749.66   639.8  778.48
   700.5  804.17   740.9  819.17   761.1  827.49   791.5  843.22     842  871.83
   862.2  881.51   882.4  888.19     933  900.91    1034     921  1064.4  927.86
#Mann= 3 , 0 , 0
       0     .06       0   526.3    .045       0   551.3     .06       0
Bank Sta=526.3,551.3
XS Rating Curve= 0 ,0
Exp/Cntr=0.3,0.1