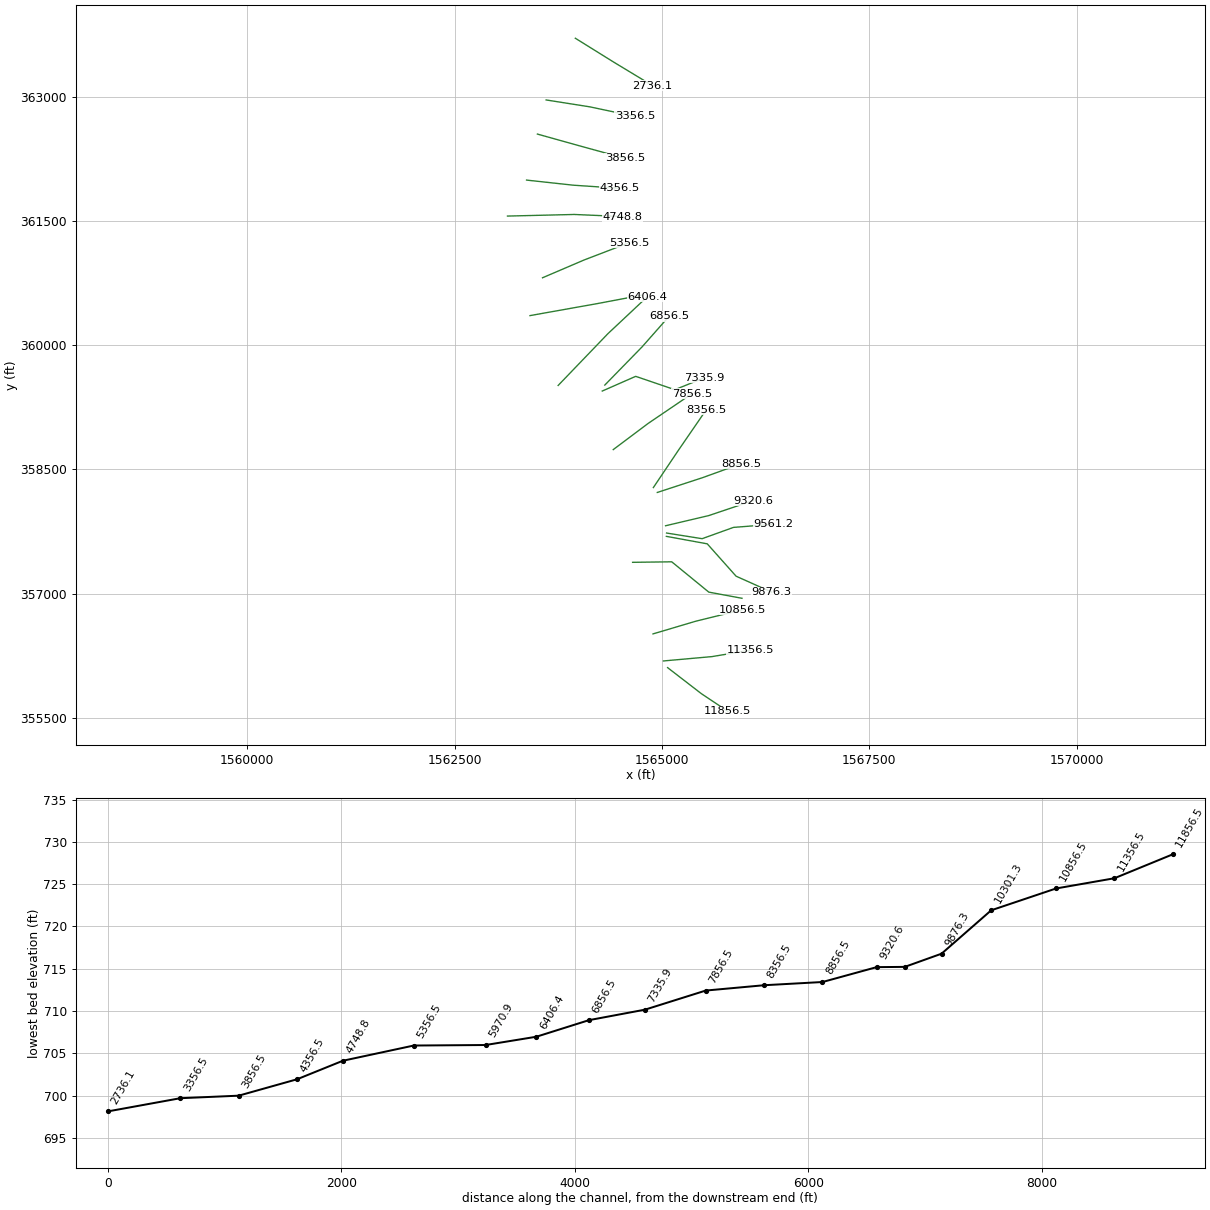
HEC-RAS study MOSESFK.prj: MOSESFK

--- MOSESFK.g01 (geometry) --- (continued)

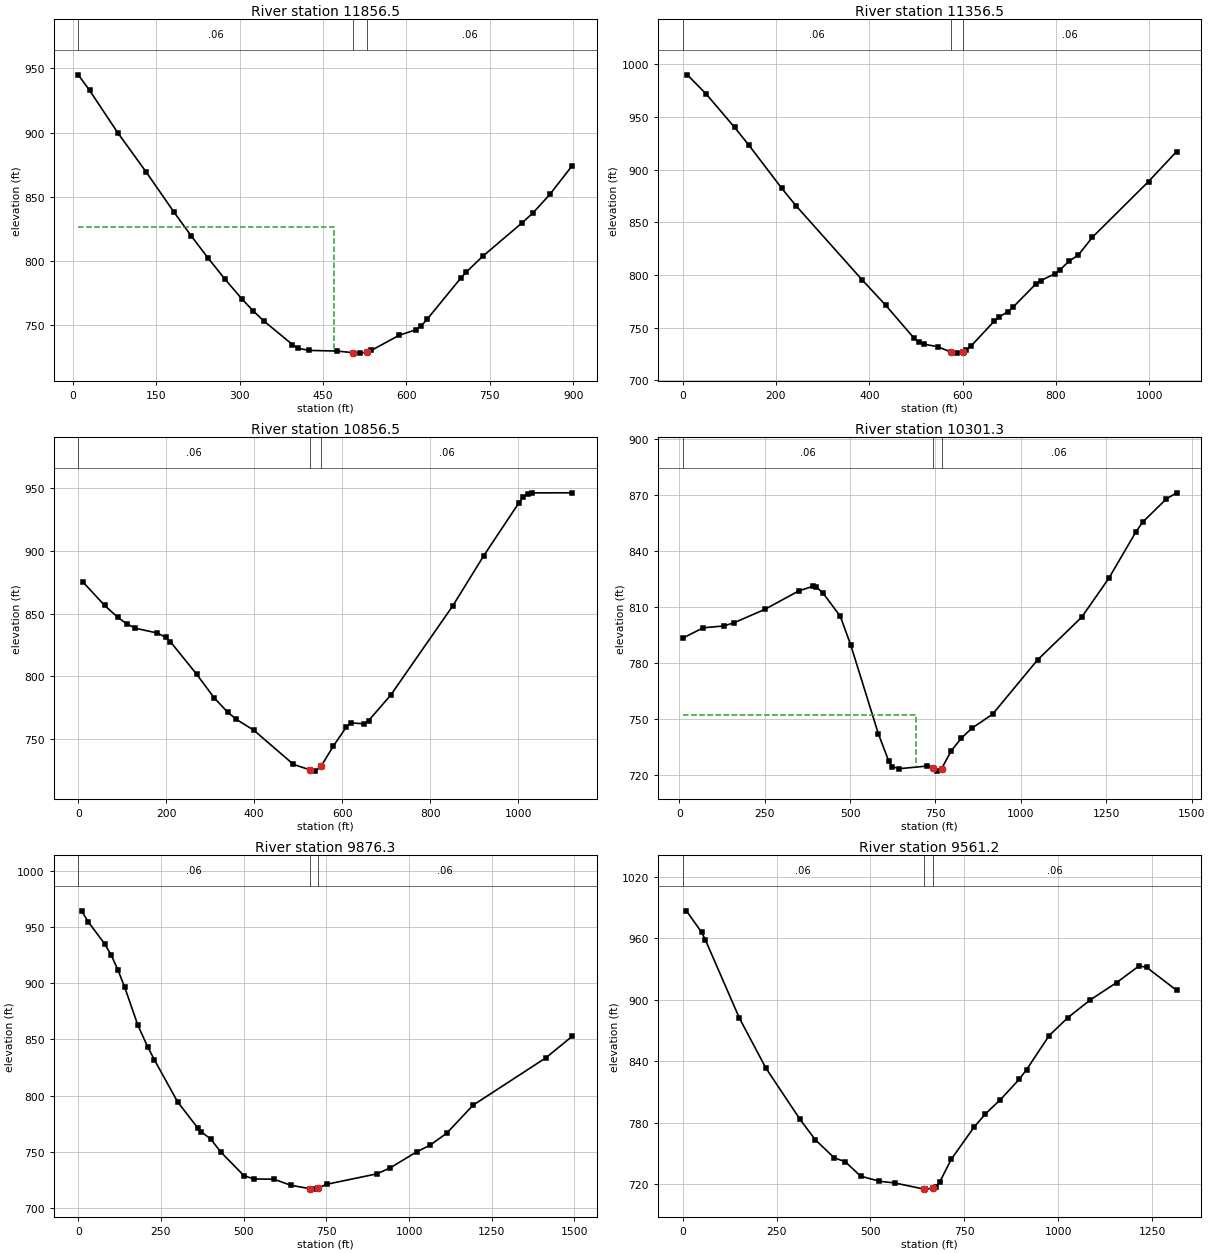
Type RM Length L Ch R = 1 ,11856.5 ,477.6,500,523.3
XS GIS Cut Line= 3
     1565068.094      356106.696     1565476.866      355790.923
     1565793.979      355579.344
#Sta/Elev= 30
    10.1  944.84    30.4  932.83      81   899.9   131.7   869.6   182.3  838.05
   212.7   819.9   243.1  802.61   273.5  786.17   303.8  770.85   324.1  761.49
   344.4  753.22     395  735.19   405.1  732.24   425.4  730.64     476  730.12
     504  728.83   516.5  728.52     529  729.33   536.6  730.57   586.8  742.39
   616.9  746.67   626.9  749.95   636.9  754.71   697.1  786.59   707.1  791.39
   737.2  803.86   807.5  829.67   827.5  837.56   857.6  851.87   897.8  874.21
#Mann= 3 , 0 , 0
    10.1     .06       0     504    .045       0     529     .06       0
#XS Ineff= 2 , 0
          469.54  826.37
Permanent Ineff=
       F       F
Bank Sta=504,529
XS Rating Curve= 0 ,0
Exp/Cntr=0.3,0.1

Type RM Length L Ch R = 1 ,11356.5 ,496.2,500,499.7
XS GIS Cut Line= 3
     1565017.536      356187.439     1565602.283      356239.968
     1566066.962      356317.637
#Sta/Elev= 30
    10.1  990.06    50.6  971.75   111.3  940.16   141.7  923.37   212.6  882.13
   242.9   865.7   384.7  795.21   435.3  771.07     496  739.74   506.1  735.86
   516.2  734.26   546.6  731.78   574.6  726.68   587.1  725.69   599.6  726.83
   607.1  728.42   617.2  732.08   667.3  755.95   677.3  759.81   697.4  765.23
   707.4  769.12   757.5   791.8   767.5  794.68   797.6  801.06   807.6  804.45
   827.7  812.98   847.7  818.85   877.8  835.76   998.1  888.72  1058.2  917.16
#Mann= 3 , 0 , 0
       0     .06       0   574.6    .045       0   599.6     .06       0
Bank Sta=574.6,599.6
XS Rating Curve= 0 ,0
Exp/Cntr=0.3,0.1

Type RM Length L Ch R = 1 ,10856.5 ,582.2,555.2,529.5
XS GIS Cut Line= 3
     1564891.977      356514.168     1565408.964      356667.808
     1565975.789      356807.471
#Sta/Elev= 30
      10  875.42    59.9  856.49    89.9  847.04   109.9   841.9   129.8  838.32
   179.8   834.5   199.8  830.95   209.7  827.49   269.7  801.48   309.6  782.63
   339.6  771.52   359.6  765.68   399.5  756.99   489.4  729.82   526.8  725.52
   539.3  724.48   551.8  728.18   579.6  744.15   609.8  759.78   619.9  762.93
     650  762.17   660.1  764.67   710.4     785   851.4  856.06   921.8  895.98
  1002.3  938.39  1012.4  942.86  1022.5  945.47  1032.5  946.19  1123.1   946.2
#Mann= 3 , 0 , 0
       0     .06       0   526.8    .045       0   551.8     .06       0
Bank Sta=526.8,551.8
XS Rating Curve= 0 ,0
Exp/Cntr=0.3,0.1

Type RM Length L Ch R = 1 ,10301.3 ,429.3,425,420.7
XS GIS Cut Line= 4
     1564646.211      357378.547     1565117.727      357384.751
     1565564.426      357018.706     1565964.328      356944.217
#Sta/Elev= 30
      10  793.26    70.2  798.82   130.4  799.81   160.5  801.53   250.8  808.74
   351.2  818.74   391.3  821.06   401.3  820.76   421.4  817.36   471.6  804.95
     502  789.63     583  741.88   613.4  727.27   623.5  724.33   643.8   723.2
   724.9  724.61   742.8  723.58   755.3   721.9   767.8  723.11   795.8  732.72
   826.2  739.64   856.6  744.92   917.4  752.47  1049.1  781.64  1178.1  804.51
  1257.4  825.35  1336.8  850.28  1356.6  855.56  1426.1     868  1455.9  871.26
#Mann= 3 , 0 , 0
      10     .06       0   742.8    .045       0   767.8     .06       0
#XS Ineff= 2 , 0
          693.51  751.88
Permanent Ineff=
       F       F
Bank Sta=742.8,767.8
XS Rating Curve= 0 ,0
Exp/Cntr=0.3,0.1

Type RM Length L Ch R = 1 ,9876.3  ,282.1,315.1,348.2
XS GIS Cut Line= 4
     1565053.055      357691.956     1565545.813      357601.897
     1565893.246      357211.035     1566321.332      357018.706
#Sta/Elev= 30
      10  964.41    30.1  954.67    80.1  934.92   100.2  924.75   120.2  911.59
   140.3  896.61   180.3  862.53   210.4  843.13   230.4  831.72   300.6  794.35
   360.7   771.4   370.7  768.04   400.7  761.27   430.8  749.81   500.9  728.76
   531.1  725.82   591.4   725.6   641.7  720.29   699.6  717.19   712.1  716.77
   724.6  717.78   752.3  721.15   903.2  730.39   943.4  735.76  1023.9  750.12
  1063.8  755.89  1113.7  766.47  1193.6  791.46  1413.3  833.55  1493.2  852.74
#Mann= 3 , 0 , 0
       0     .06       0   699.6    .045       0   724.6     .06       0
Bank Sta=699.6,724.6
XS Rating Curve= 0 ,0
Exp/Cntr=0.3,0.1

Type RM Length L Ch R = 1 ,9561.2  ,243,240.6,240.1
XS GIS Cut Line= 4
     1565055.686      357732.184     1565483.772      357663.938
     1565862.225       357800.43     1566339.945      357837.654
#Sta/Elev= 30
    10.1  986.54    50.4  965.67    60.5  958.24   151.2  881.84   221.8  833.12
   312.5  783.25   352.8  763.49   403.2  745.86   433.5  741.78   473.7  727.88
     524  722.88   564.2  721.25   642.3  715.27   644.7  715.21   667.3   716.2
   674.9  717.71   684.9  722.43   715.1  744.32   775.5   775.5   805.6  788.39
   845.8  802.39   895.7  822.14   915.7  831.71   975.6  864.84  1025.5   882.4
  1085.4  899.74  1155.3  916.58  1215.1  932.82  1235.1   931.5    1315  909.02
#Mann= 3 , 0 , 0
       0     .06       0   642.3    .045       0   667.3     .06       0
Bank Sta=642.3,667.3
XS Rating Curve= 0 ,0
Exp/Cntr=0.3,0.1

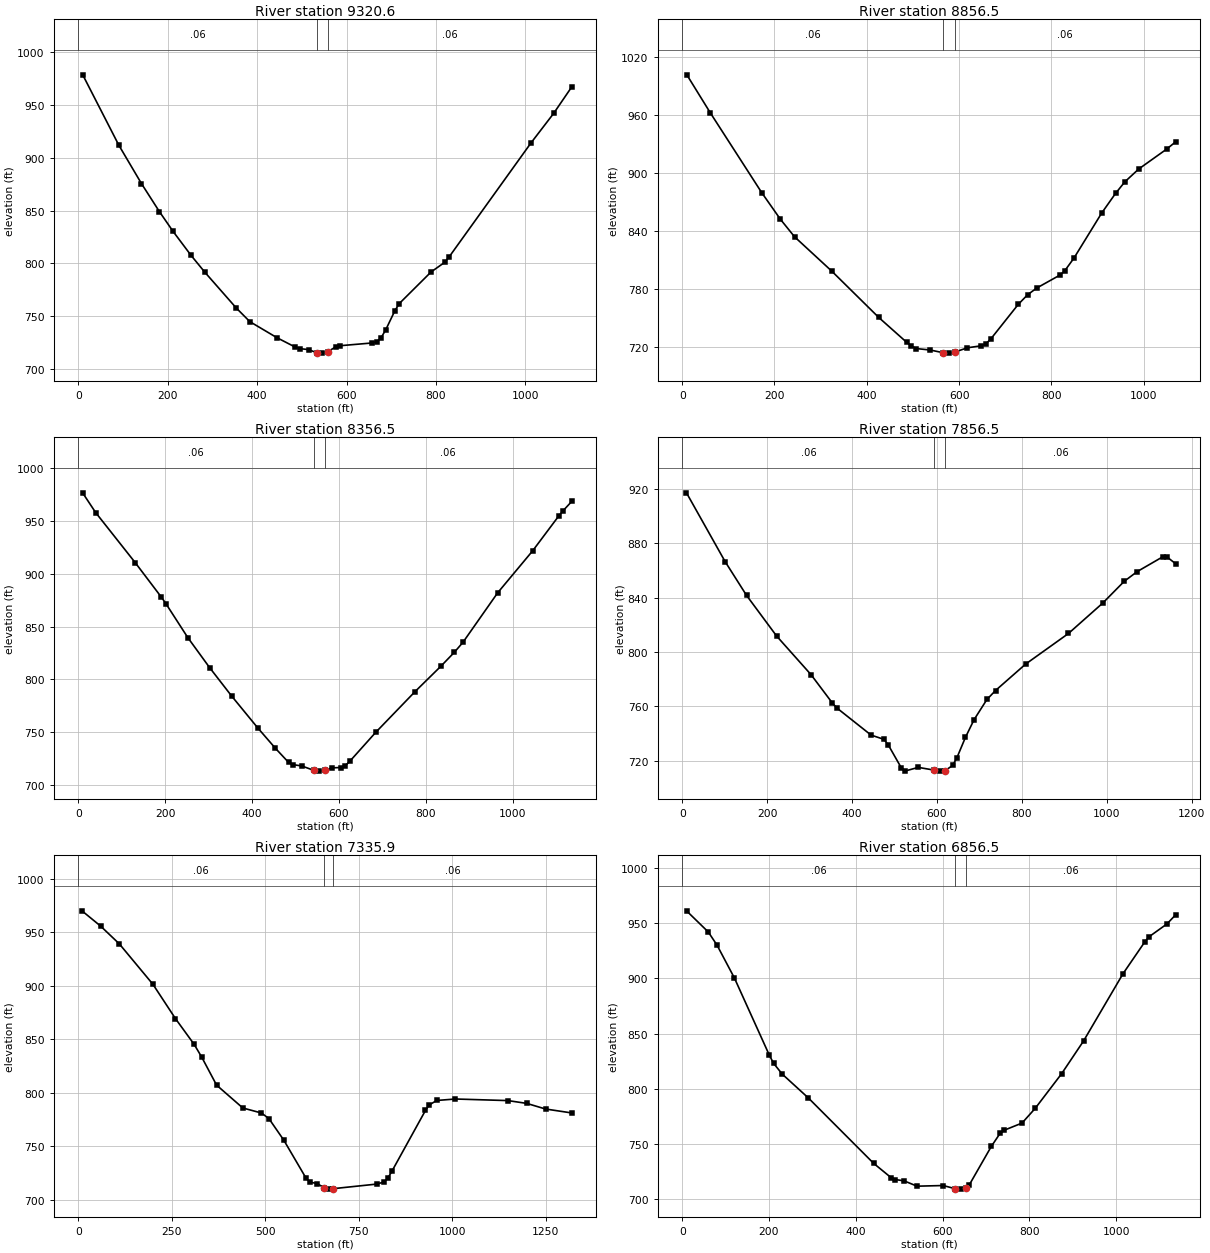
Type RM Length L Ch R = 1 ,9320.6  ,462.5,464.1,464.5
XS GIS Cut Line= 3
     1565043.626      357820.051     1565564.426      357943.125
     1566102.873      358124.919
#Sta/Elev= 30
    10.1  978.47    90.9   911.8   141.4  875.58   181.7  848.94     212  830.38
   252.4  807.59   282.7  791.92   353.4  757.85   383.7  744.97   444.3  729.78
   484.7     721   494.8  719.44     515  718.55   532.8  715.61   545.3  715.18
   557.8  716.53   575.7  721.07   585.9  722.21   656.9  724.79   667.1  725.93
   677.2   729.8   687.4  737.12   707.7  755.06   717.8  762.06   788.9  791.96
   819.3  801.06   829.4  806.29  1012.1  913.92  1062.9  941.95  1103.5  967.09
#Mann= 3 , 0 , 0
       0     .06       0   532.8    .045       0   557.8     .06       0
Bank Sta=532.8,557.8
XS Rating Curve= 0 ,0
Exp/Cntr=0.3,0.1

Type RM Length L Ch R = 1 ,8856.5  ,481.9,500,517
XS GIS Cut Line= 3
     1564944.011      358222.312     1565493.245      358402.255
     1565955.287      358569.744
#Sta/Elev= 30
    10.1 1001.14    60.8  961.94   172.4  879.27   212.9  851.74   243.4  833.72
   324.5     798   425.9  750.29   486.7  724.47   496.8  720.73     507  718.15
   537.4  716.64   565.5  713.84     578  713.42   590.5   714.5   618.1  718.96
   648.2     721   658.2  723.18   668.2   727.8   728.4  763.96   748.5  773.81
   768.5   780.8   818.7  794.16   828.7  798.42   848.8  811.64   908.9  858.22
     939  878.57   959.1  890.51   989.2  903.78  1049.4  924.24  1069.4  931.94
#Mann= 3 , 0 , 0
       0     .06       0   565.5    .045       0   590.5     .06       0
Bank Sta=565.5,590.5
XS Rating Curve= 0 ,0
Exp/Cntr=0.3,0.1

Type RM Length L Ch R = 1 ,8356.5  ,508.9,500,490.2
XS GIS Cut Line= 3
     1564896.344      358281.424     1565205.083      358742.075
     1565534.188      359221.218
#Sta/Elev= 30
    10.1  976.67    40.3  957.89   131.1  910.58   191.6   877.7   201.7  871.75
   252.1  839.58   302.5  811.03   352.9  784.26   413.4  753.86   453.7  734.71
     484  721.35     494   719.2   514.2  717.96     542  713.81   554.5  713.04
     567  714.06   584.6  716.14   604.7  716.47   614.7  718.21   624.7  722.25
   684.8  749.85     775  788.32   835.2  812.66   865.2  825.46   885.3  835.01
   965.5   882.1  1045.6  921.65  1105.8  954.71  1115.8   959.7  1135.8  968.58
#Mann= 3 , 0 , 0
       0     .06       0     542    .045       0     567     .06       0
Bank Sta=542,567
XS Rating Curve= 0 ,0
Exp/Cntr=0.3,0.1

Type RM Length L Ch R = 1 ,7856.5  ,547.7,520.6,494.9
XS GIS Cut Line= 3
     1564412.951      358739.702      1564833.16      359055.599
     1565359.689      359413.509
#Sta/Elev= 30
    10.1  917.28   101.1  866.66   151.6  841.76   222.4  811.85   303.3  783.48
   353.8   762.5   363.9  758.98   444.8  738.95   475.2   735.8   485.3  731.72
   515.6  715.07   525.7  712.55     556  715.17   594.1  713.12   606.6  712.41
   619.1  712.78   636.9  716.57     647  722.26   667.2  737.33   687.4  750.28
   717.7  765.16   737.9  771.74   808.7  791.17   909.7  813.73   990.6  836.16
  1041.1  852.15  1071.4  859.26    1132  870.22  1142.2  869.99  1162.4     865
#Mann= 3 , 0 , 0
       0     .06       0   594.1    .045       0   619.1     .06       0
Bank Sta=594.1,619.1
XS Rating Curve= 0 ,0
Exp/Cntr=0.3,0.1

Type RM Length L Ch R = 1 ,7335.9  ,447.8,479.4,512.4
XS GIS Cut Line= 4
     1564280.706      359447.087     1564683.436       359624.45
     1565154.952      359463.142     1565508.589      359605.837
#Sta/Elev= 30
      10  970.12      60  955.83     110  939.21     200  901.37     260  869.43
     310  845.37     330   833.6     370   807.3   440.1  785.95   489.9  781.26
   509.8  776.08   549.7  755.89   609.5  720.21   619.5  716.75   639.4  715.28
   656.8  711.54   669.3  710.15   681.8  710.58   798.9  714.89   818.8  716.98
   828.8  720.93   838.7  726.84   928.4   783.6   938.4  788.75   958.5  792.96
  1008.6  794.34  1149.1  792.85  1199.3  790.24  1249.5  784.99  1319.7  781.31
#Mann= 3 , 0 , 0
       0     .06       0   656.8    .045       0   681.8     .06       0
Bank Sta=656.8,681.8
XS Rating Curve= 0 ,0
Exp/Cntr=0.3,0.1

Type RM Length L Ch R = 1 ,6856.5  ,450.4,450.2,447.4
XS GIS Cut Line= 3
     1564311.187      359518.979     1564758.692      359978.566
     1565086.706      360350.336
#Sta/Elev= 30
      10  961.28    60.1   942.1    80.2  930.21   120.3  900.39   200.5  830.65
   210.5  823.05   230.5  813.23   290.7  791.59     441  732.34   481.1  719.42
   491.1   717.6   511.2  716.43   541.2  711.58   601.4  712.18     629  709.29
   641.5  708.91     654  710.27   661.7  712.87   712.3  747.63   732.5  759.47
   742.6  762.42   783.1  768.82   813.5  782.18   874.2  813.52   924.8  843.23
  1015.8  904.27  1066.4  933.35  1076.5  937.96    1117  949.39  1137.3  957.76
#Mann= 3 , 0 , 0
       0     .06       0     629    .045       0     654     .06       0
Bank Sta=629,654
XS Rating Curve= 0 ,0
Exp/Cntr=0.3,0.1

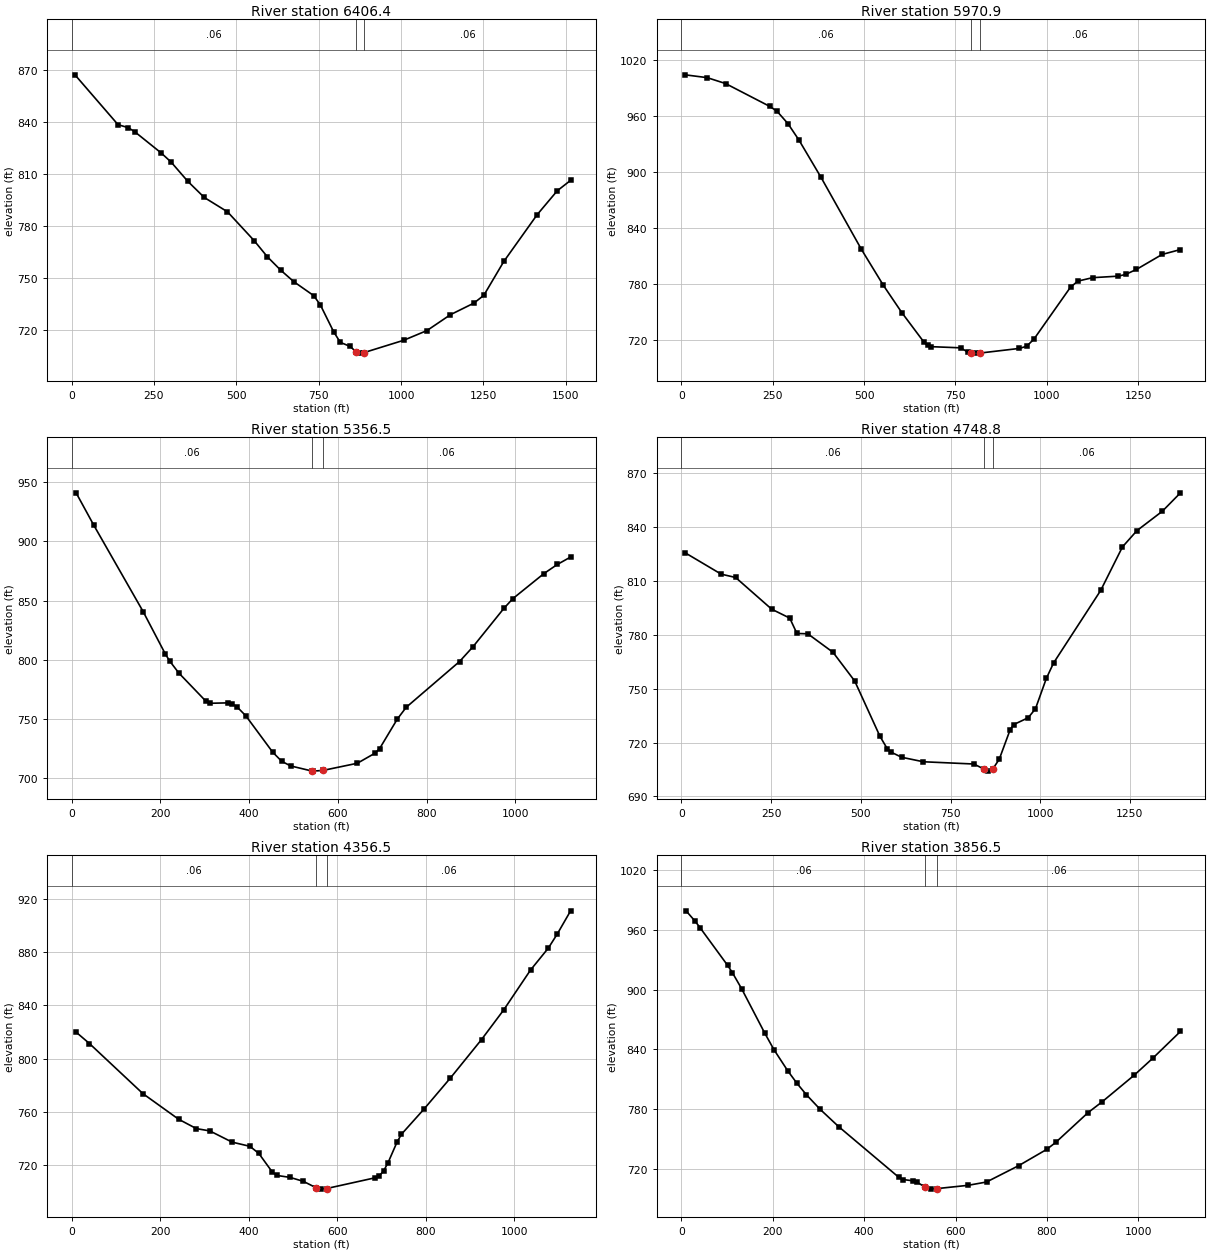
Type RM Length L Ch R = 1 ,6406.4  ,448,435.5,433.4
XS GIS Cut Line= 3
     1563748.936       359514.52     1564348.412      360139.394
     1564821.041      360583.934
#Sta/Elev= 30
    10.1  867.19     141  838.47   171.2  836.82   191.3  834.47   271.9   822.2
   302.1  816.94   352.4  805.93   402.8  796.56   473.2  788.31   553.8  771.79
   594.1  762.45   634.3  754.79   674.6  748.07     735  740.04   755.2  734.67
   795.4  719.26   815.6  713.15   845.8  710.79   863.6  707.63   876.1  706.95
   888.6  707.31  1007.9  714.34  1078.8  719.95  1149.8  729.06  1220.8  735.71
  1251.2   740.2    1312  759.73  1413.4  786.72  1474.2  800.42  1514.8  806.44
#Mann= 3 , 0 , 0
       0     .06       0   863.6    .045       0   888.6     .06       0
Bank Sta=863.6,888.6
XS Rating Curve= 0 ,0
Exp/Cntr=0.3,0.1

Type RM Length L Ch R = 1 ,5970.9  ,613.2,614.3,605.1
XS GIS Cut Line= 3
     1563409.647      360357.897     1564221.438      360503.065
     1564753.675      360603.793
#Sta/Elev= 30
    10.1  1004.3    70.4 1001.27   120.7  994.97   241.4  970.54   261.5  965.35
   291.7  951.92   321.8  934.32   382.2  894.36   492.8  817.18   553.1  778.53
   603.4  749.41   663.8  717.85   673.8  714.17   683.9  712.89   764.3  711.65
   784.4  707.03   792.1  706.35   804.6  705.97   817.1  706.03     925     711
     945  713.29   965.1  720.92  1065.4  776.73  1085.5  783.16  1125.6  786.85
  1195.8  788.48  1215.9  790.28    1246  795.73  1316.2  811.76  1366.4     817
#Mann= 3 , 0 , 0
       0     .06       0   792.1    .045       0   817.1     .06       0
Bank Sta=792.1,817.1
XS Rating Curve= 0 ,0
Exp/Cntr=0.3,0.1

Type RM Length L Ch R = 1 ,5356.5  ,620.8,607.7,605.4
XS GIS Cut Line= 3
     1563560.678       360814.91     1564060.462      361029.099
     1564602.783      361237.529
#Sta/Elev= 30
    10.1  941.02    50.3  913.44   161.1  840.76   211.5  804.67   221.5   798.7
   241.7  788.76   302.1   765.2   312.2  763.23   352.4  763.58   362.5  762.53
   372.6  760.27   392.7  752.62   453.1  721.98   473.3  714.28   493.4  710.33
   541.3  706.03   543.7  705.91   566.3  706.49   643.9  712.55     684  721.11
     694  724.83   734.1   749.9   754.1  759.82   874.3   798.5   904.4  810.88
   974.5  843.51   994.5  851.63  1064.6  872.83  1094.7   880.5  1124.7   886.8
#Mann= 3 , 0 , 0
       0     .06       0   541.3    .045       0   566.3     .06       0
Bank Sta=541.3,566.3
XS Rating Curve= 0 ,0
Exp/Cntr=0.3,0.1

Type RM Length L Ch R = 1 ,4748.8  ,394.2,392.3,391.5
XS GIS Cut Line= 3
     1563138.215      361559.951     1563942.816      361579.339
     1564528.333      361553.941
#Sta/Elev= 30
    10.1  825.71   110.7  813.79   150.9  811.94   251.5  794.28   301.8  789.32
   321.9  780.75   352.1  780.59   422.5  770.26   482.9  754.29   553.3  723.49
   573.4  716.66   583.5  714.76   613.7  711.83     674  709.33   814.9  708.07
   842.9   705.3   855.4  704.11   867.9  705.37   885.7  710.68     916  727.07
   926.1  730.03   966.5  733.85   986.7  738.82    1017  755.71  1037.2  764.33
  1168.6  804.74  1229.2  828.95  1269.6  838.03  1340.4  848.82  1390.9  859.07
#Mann= 3 , 0 , 0
       0     .06       0   842.9    .045       0   867.9     .06       0
Bank Sta=842.9,867.9
XS Rating Curve= 0 ,0
Exp/Cntr=0.3,0.1

Type RM Length L Ch R = 1 ,4356.5  ,505.3,500,493.7
XS GIS Cut Line= 3
     1563368.156      361994.435     1563928.818       361933.05
     1564491.108      361895.169
#Sta/Elev= 30
    10.1  819.96    40.3  811.38   161.1  773.71   241.7  754.48     282  747.41
   312.2   745.7   362.6  737.26   402.9  734.11     423  728.76   453.2  714.89
   463.3  712.24   493.5  710.75   523.7  707.77   551.5  703.13     564  701.92
   576.5  702.39   684.8  710.37   694.8  711.79   704.9  715.55     715  721.77
   735.1   737.1   745.2  743.14   795.5   761.8   855.9  785.45   926.3   814.4
   976.6  836.76    1037  866.65  1077.3  883.17  1097.4  893.73  1127.6  911.16
#Mann= 3 , 0 , 0
       0     .06       0   551.5    .045       0   576.5     .06       0
Bank Sta=551.5,576.5
XS Rating Curve= 0 ,0
Exp/Cntr=0.3,0.1

Type RM Length L Ch R = 1 ,3856.5  ,496.6,500,501.8
XS GIS Cut Line= 3
     1563498.908      362550.115     1564025.243       362402.96
     1564551.592      362258.141
#Sta/Elev= 30
    10.1  978.87    30.4   968.2    40.5   962.1   101.2  924.12   111.3  917.06
   131.6  900.92   182.2  856.43   202.4   839.8   232.8  818.47     253  805.93
   273.3  794.67   303.6  779.96   344.1  762.63   475.7  711.86   485.8  709.54
     506  708.38   516.2  706.77     534  701.91   546.5  699.98     559  700.49
   627.4  703.79   667.8  707.11   738.6  723.59   799.3  739.72   819.5  746.86
   890.2  776.69   920.6  787.36   991.3  814.22  1031.8  831.16  1092.4  858.01
#Mann= 3 , 0 , 0
       0     .06       0     534    .045       0     559     .06       0
Bank Sta=534,559
XS Rating Curve= 0 ,0
Exp/Cntr=0.3,0.1

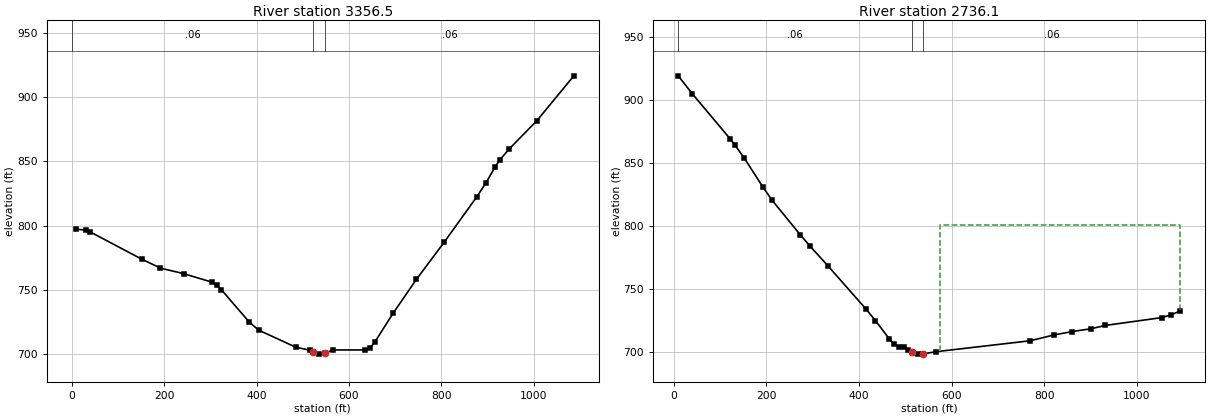
Type RM Length L Ch R = 1 ,3356.5  ,631.6,620.4,610.9
XS GIS Cut Line= 3
     1563603.914      362962.283     1564132.919      362878.679
     1564672.023      362763.733
#Sta/Elev= 30
    10.1  797.09    30.3  796.46    40.4  794.93   151.6  773.73     192  766.78
   242.5  762.42   303.2  755.86   313.3  753.51   323.4  750.09     384  724.78
   404.2  718.47     485  705.06   515.4  702.76   523.1  701.31   535.6  699.68
   548.1  700.43   565.6  702.94   635.8  702.95   645.8  704.58   655.8     709
   695.9  731.77     746  757.99   806.2  787.02   876.3   822.2   896.4  833.21
   916.4  845.76   926.4  851.09   946.5  859.62  1006.6  881.72  1086.8  916.79
#Mann= 3 , 0 , 0
       0     .06       0   523.1    .045       0   548.1     .06       0
Bank Sta=523.1,548.1
XS Rating Curve= 0 ,0
Exp/Cntr=0.3,0.1

Type RM Length L Ch R = 1 ,2736.1  ,367.8,379.6,391.9
XS GIS Cut Line= 3
     1563955.965      363707.495     1564420.188      363418.055
     1564887.651      363134.821
#Sta/Elev= 30
    10.1  919.13    40.5  904.86   121.6  869.32   131.7  864.52     152  854.17
   192.5  830.97   212.7   820.3   273.5  792.85   293.8  784.17   334.3  767.76
   415.4  733.86   435.6  724.77     466  710.02   476.1  706.09   486.3   704.1
   496.4  703.55   506.5  701.76   514.3  699.68   516.7  699.04   526.8  698.12
   539.3  698.36   567.3  700.09   769.7  708.73   820.3   713.3   860.8  716.06
   901.3   718.3   931.7  720.91  1053.1  727.11  1073.4  729.31  1093.6  732.41
#Mann= 3 , 0 , 0
    10.1     .06       0   514.3    .045       0   539.3     .06       0
#XS Ineff= 2 , 0
                          575.63          800.55
Permanent Ineff=
       F       F
Bank Sta=514.3,539.3
XS Rating Curve= 0 ,0
Exp/Cntr=0.3,0.1