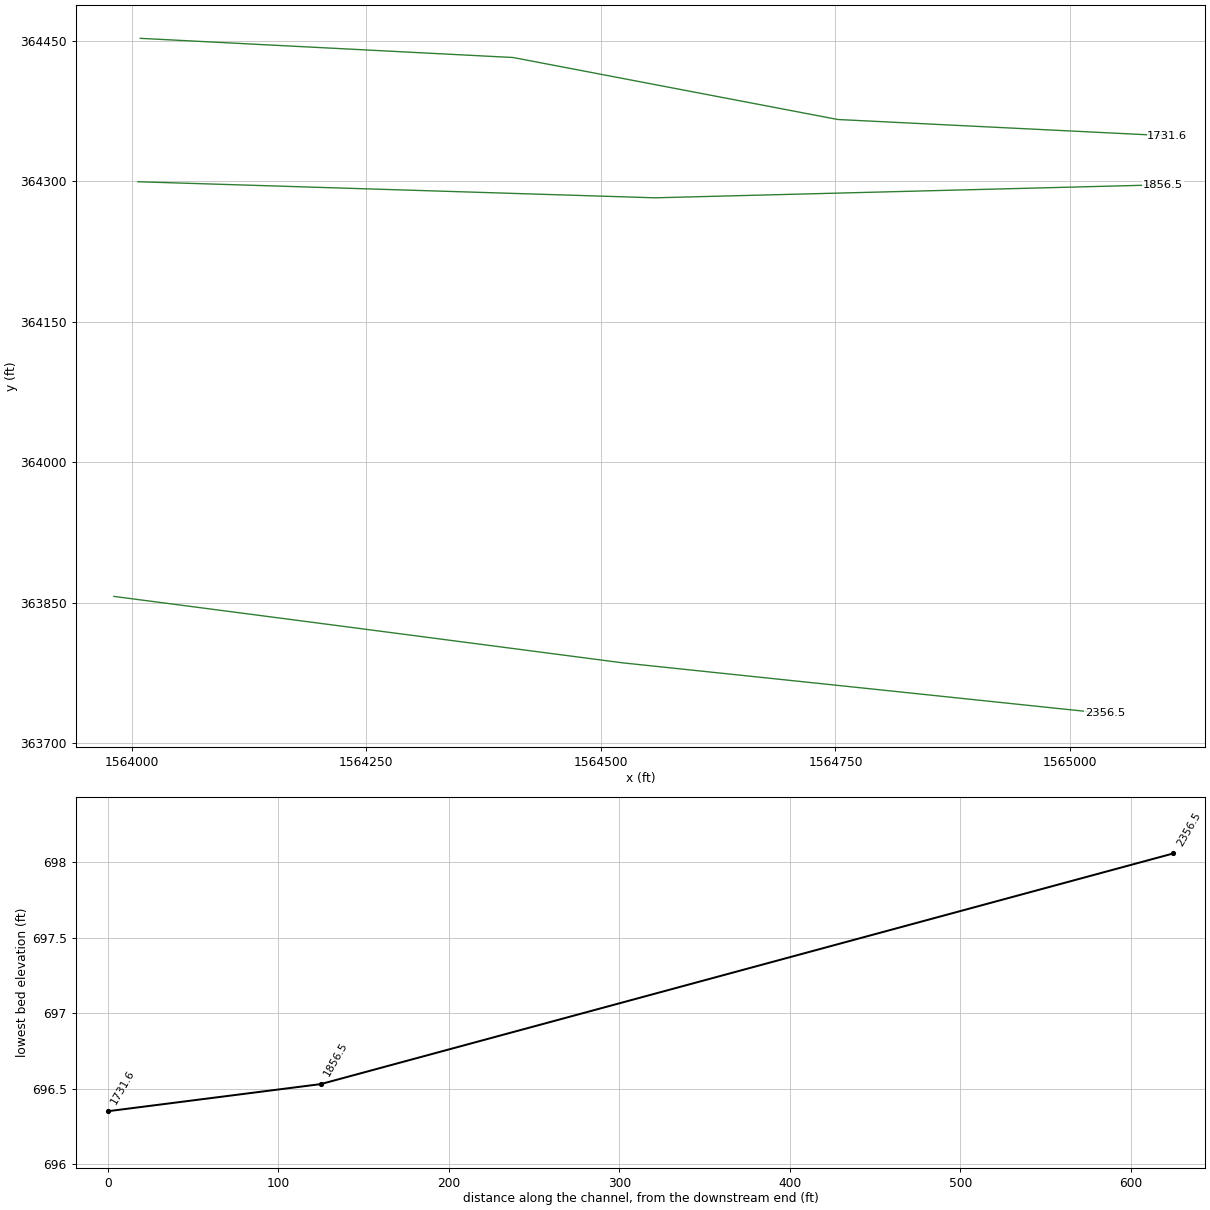
HEC-RAS study MOSESFK.prj: MOSESFK

--- MOSESFK.g01 (geometry) --- (continued)

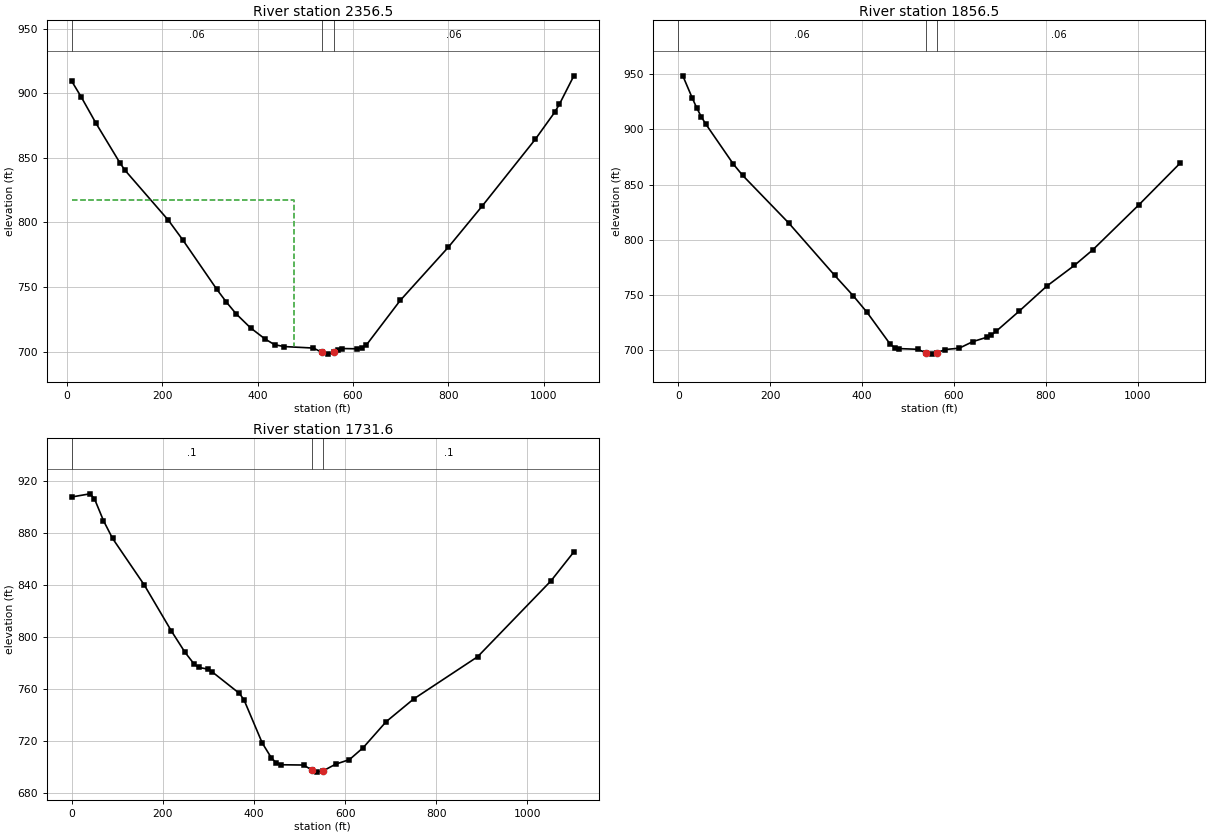
Type RM Length L Ch R = 1 ,2356.5  ,497.2,500,503.7
XS GIS Cut Line= 3
     1563981.065       363856.52     1564523.871      363785.493
     1565037.073      363731.598
#Sta/Elev= 30
    10.1  909.31    30.4  896.83    60.8  876.86   111.5  845.89   121.7  840.43
   212.9  801.66   243.3  786.34   314.3  748.27   334.5  738.34   354.8  729.31
   385.2  718.38   415.6  709.79   435.9  705.29   456.2  703.91     517  702.76
   534.9  699.44   547.4  698.06   559.9  699.81   567.7   701.4   577.8  702.38
   608.1  702.19   618.3  702.76   628.4  705.22   699.2  739.62   800.4  780.94
   871.2   812.7   982.5  864.32    1023  885.13  1033.1  891.45  1063.5  913.51
#Mann= 3 , 0 , 0
    10.1     .06       0   534.9    .045       0   559.9     .06       0
#XS Ineff= 2 , 0
          476.65  817.03
Permanent Ineff=
       F       F
Bank Sta=534.9,559.9
XS Rating Curve= 0 ,0
Exp/Cntr=0.3,0.1

Type RM Length L Ch R = 1 ,1856.5  ,122.5,124.9,125.5
XS GIS Cut Line= 3
     1564006.595      364299.416     1564557.701      364282.242
     1565099.114      364296.176
#Sta/Elev= 30
      10  948.52    30.1  928.83    40.1  919.62    50.1   911.5    60.1  904.77
   120.3  868.42   140.3  858.35   240.6  815.22   340.8  767.73   380.9  749.39
     411  734.38   461.1  705.72   471.2  702.23   481.2  701.53   521.3  700.91
   538.9  697.76   551.4  696.53   563.9  697.91   581.5  700.72   611.6   701.9
   641.6   707.9   671.7  711.79   681.8  713.97   691.8  717.11   741.9  735.32
   802.1  758.04   862.3  776.83   902.4  790.94  1002.7  831.66    1093  869.62
#Mann= 3 , 0 , 0
       0     .06       0   538.9    .045       0   563.9     .06       0
Bank Sta=538.9,563.9
XS Rating Curve= 0 ,0
Exp/Cntr=0.3,0.1

Type RM Length L Ch R = 1 ,1731.6  ,1836,1731.6,1819.2
XS GIS Cut Line= 4
     1564009.114      364452.568     1564406.439      364432.082
     1564752.542      364365.881     1565103.661      364348.509
#Sta/Elev= 30
       0  907.95    39.8  910.36    49.7  906.64    69.6  889.72    89.5  876.09
   159.1  840.27   218.8  804.76   248.7  788.38   268.6  779.42   278.5   776.9
   298.4  775.56   308.3  773.39     368  756.85     378  751.89     418  718.74
   438.1  707.28   448.2  703.69   458.3  702.02   508.6  701.81   526.3  698.14
   538.8  696.35   551.3  697.28   579.1  702.47   609.3  705.96   639.5  715.16
   689.8   735.1   750.2  752.58   890.8  785.13  1051.6  843.42  1101.8  865.69
#Mann= 3 , 0 , 0
       0      .1       0   526.3    .045       0   551.3      .1       0
Bank Sta=526.3,551.3
XS Rating Curve= 0 ,0
Exp/Cntr=0.3,0.1
Stream Node=MOSESFK         ,Main            , 0 , 0 ,Upstream end
Stream Node=MOSESFK         ,Main            , 0 , 1 ,Downstream end

Chan Stop Cuts=-1
Use User Specified Reach Order=0